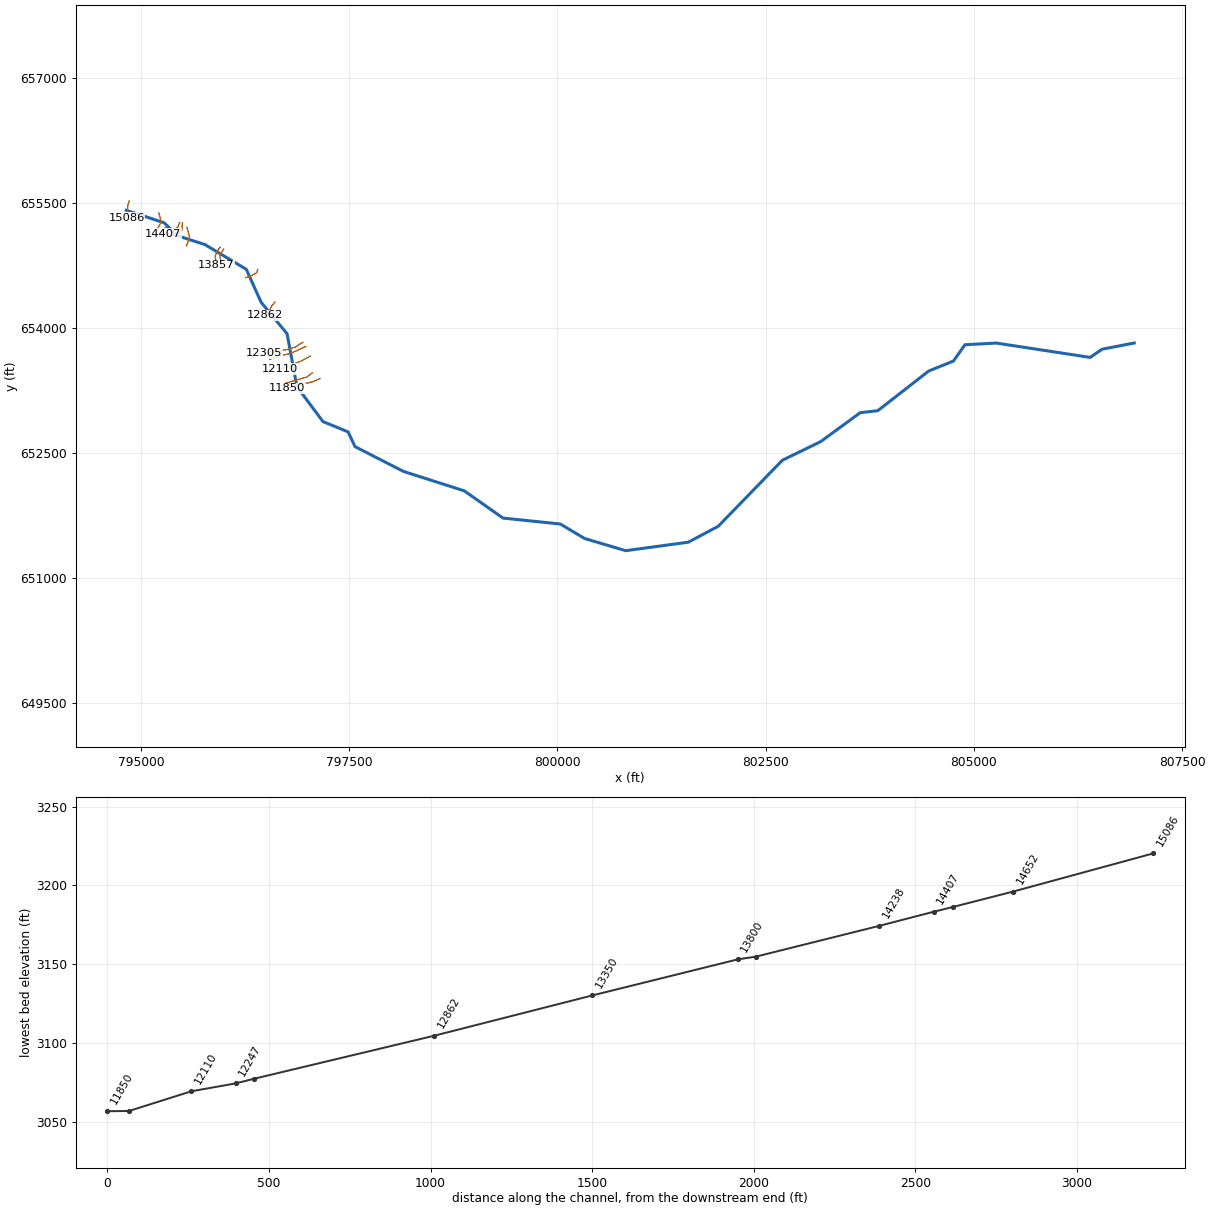
--- lds_plott_crk.prj (project) ---

Proj Title=Plott Creek Limited Detail Study
Current Plan=p02
Default Exp/Contr=0.3,0.1
English Units
Geom File=g01
Flow File=f02
Plan File=p02
Y Axis Title=Elevation
X Axis Title(PF)=Main Channel Distance
X Axis Title(XS)=Station
BEGIN DESCRIPTION:
 Plott Creek
END DESCRIPTION:
DSS File=dss
DSS Export Rating Curves= 0
DSS Export Rating Curve Sorted= 0
DSS Export Volume Flow Curves= 0
DXF OffsetX= 0
DXF OffsetY= 0
DXF ScaleX= 1
DXF ScaleY= 10

--- lds_plott_crk.p02 (plan) ---

Plan Title=Floodway Run
Program Version=3.13
Short Identifier=Floodway Run
Geom File=g01
Flow File=f02
Subcritical Flow
K Sum by GR= 0
Std Step Tol= 0.01
Critical Tol= 0.01
Num of Std Step Trials= 20
Max Error Tol= 0.3
Flow Tol Ratio= 0.001
Split Flow NTrial= 30
Split Flow Tol= 0.02
Split Flow Ratio= 0.02
Log Output Level= 0
Friction Slope Method= 1
Unsteady Friction Slope Method= 2
Unsteady Bridges Friction Slope Method= 1
Parabolic Critical Depth
Global Vel Dist= 0 , 0 , 0
Global Log Level= 0
CheckData=True
Encroach Param=-1 ,7,7, 2
Encroach River=Plott Creek
Encroach Reach=Reach-1
Encroach Node=15086
       4      .5
Encroach Node=14652
       1  4976.5  5019.4
Encroach Node=14468
       1  4942.2  5047.1
Encroach Node=14407
       1  4922.1 5027.21
Encroach Node=14238
       1 4983.02 5028.01
Encroach Node=13857
       1 4986.01 5020.81
Encroach Node=13800
       1 4977.16    5019
Encroach Node=13350
       1  4986.5  5019.5
Encroach Node=12862
       1 4990.46  5022.8
Encroach Node=12305
       1    4963  5031.9
Encroach Node=12247
       1  4968.1 5024.78
Encroach Node=12110
       4      .7
Encroach Node=11917
       4      .7
Encroach Node=11850
       4      .7
Encroach Node=11705
       1  4973.5  5020.3
Encroach Node=11502
       1 4968.64  5030.6
Encroach Node=11468
       1    4974    5016
Encroach Node=10996
       1  4978.1    5030
Encroach Node=10513
       1  4937.5    5063
Encroach Node=10191
       1    4940    5029
Encroach Node=10133
       1    4940    5025
Encroach Node=9773
       1    4981    5025
Encroach Node=9500
       1    4969    5065
Encroach Node=9435
       1    4970  5055.3
Encroach Node=9274
       4      .7
Encroach Node=9097
       4      .7
Encroach Node=9045
       1    4965    5041
Encroach Node=8729
       4      .7
Encroach Node=8387
       4      .7
Encroach Node=8335
       1  4978.4    5120
Encroach Node=7781
       1    4951    5050
Encroach Node=7302
       1    4900    5014
Encroach Node=6716
       1    4870    5062
Encroach Node=6657
       1  4855.1    5015
Encroach Node=6035
       1 4923.44    5011
Encroach Node=5467
       4      .7
Encroach Node=5031
       4      .7
Encroach Node=4553
       1  4989.6    5164
Encroach Node=4465
       1    4965    5112
Encroach Node=4088
       4      .7
Encroach Node=3822
       1  4973.1    5062
Encroach Node=3678
       1  4980.3 5019.95
Encroach Node=3231
       1    4943  5053.3
Encroach Node=2831
       1  4976.5    5086
Encroach Node=2744
       1  4981.4    5085
Encroach Node=2399
       1  4936.6 5047.49
Encroach Node=2301
       1  4968.9    5127
Encroach Node=2031
       1    4956 5047.71
Encroach Node=1815
       1  4946.5    5075
Encroach Node=1781
       1    4950    5105
Encroach Node=1639
       1    4959    5077
Encroach Node=1603
       1  4960.1  5076.6
Encroach Node=1303
       1  4945.3  5048.5
Encroach Node=969
       1    4900  5037.5
Encroach Node=909
       1    4883 5027.78
Encroach Node=868
       1 4959.74    5070
Encroach Node=686
       1    4900    5054
Encroach Node=443
       1 4973.05  5142.9
Encroach Node=252
       1    4961    5027
Encroach Node=160
       1    4972    5019
BEGIN DESCRIPTION:
Floodway Run
END DESCRIPTION:
Computation Interval=1HOUR
Output Interval=1HOUR
Run HTab= 0
Run UNet= 0
Run PostProcess= 0
UNET Theta= 1
UNET Theta Warmup= 1
UNET ZTol= 0.02
UNET ZSATol= 0.05
UNET MxIter= 20
UNET MaxInSteps= 0
UNET DtIC= 0
UNET DtMin= 0
UNET MaxCRTS= 20
UNET WFStab= 2
UNET SFStab= 1
UNET WFX= 1
UNET SFX= 1
UNET DSS MLevel= 4
UNET DZMax Abort= 100
UNET Convert EG Bridges=-1
UNET Use Existing IB Tables=-1
UNET Froude Reduction=False
UNET Froude Limit= 1
UNET Froude Power= 10
Instantaneous Interval=1HOUR
DSS File=dss
Write IC File= 0
Echo Input=False
Echo Output=False
Write Detailed= 0
Detailed Automatic Start=False, 10

--- lds_plott_crk.f02 (steady flow) ---

Flow Title=Floodway
Program Version=3.13
Number of Profiles= 2
Profile Names=100-year,100-FW
River Rch & RM=Plott Creek,Reach-1         ,15086
    1140    1140
River Rch & RM=Plott Creek,Reach-1         ,14468
    1460    1460
River Rch & RM=Plott Creek,Reach-1         ,10996
    1590    1590
River Rch & RM=Plott Creek,Reach-1         ,5031
    1710    1710
Boundary for River Rch & Prof#=Plott Creek,Reach-1         , 1
Up Type= 0
Dn Type= 3
Dn Slope=0.0325
Boundary for River Rch & Prof#=Plott Creek,Reach-1         , 2
Up Type= 0
Dn Type= 3
Dn Slope=0.0325
DSS Import GetInterval= 0
DSS Import GetPeak= 0
DSS Import FillOption= 0

--- lds_plott_crk.g01 (geometry) ---

Geom Title=Existing Conditions
Program Version=3.13

River Reach=Plott Creek     ,Reach-1
Reach XY= 30
       794822.42       655413.27       795276.56       655263.09
       795439.45       655106.67       795765.22       655001.96
       796262.93       654704.62       796441.33       654307.75
       796752.88       653930.27       796870.52       653295.53
       797183.36       652875.39       797485.87       652751.29
        797568.6       652574.18       798149.06       652277.05
       798881.11       652042.71       799346.46       651715.73
        800033.4       651644.72       800326.63       651470.26
       800819.54       651324.17         801571.       651426.11
       801930.44        651617.4       802699.76       652409.84
       803161.15       652634.75       803635.15       652981.58
        803846.4       653005.75       804457.02       653481.85
        804755.5       653602.72       804893.18        653798.2
       805269.44       653818.17       806396.55       653645.94
        806539.4       653744.14       806925.82       653818.91

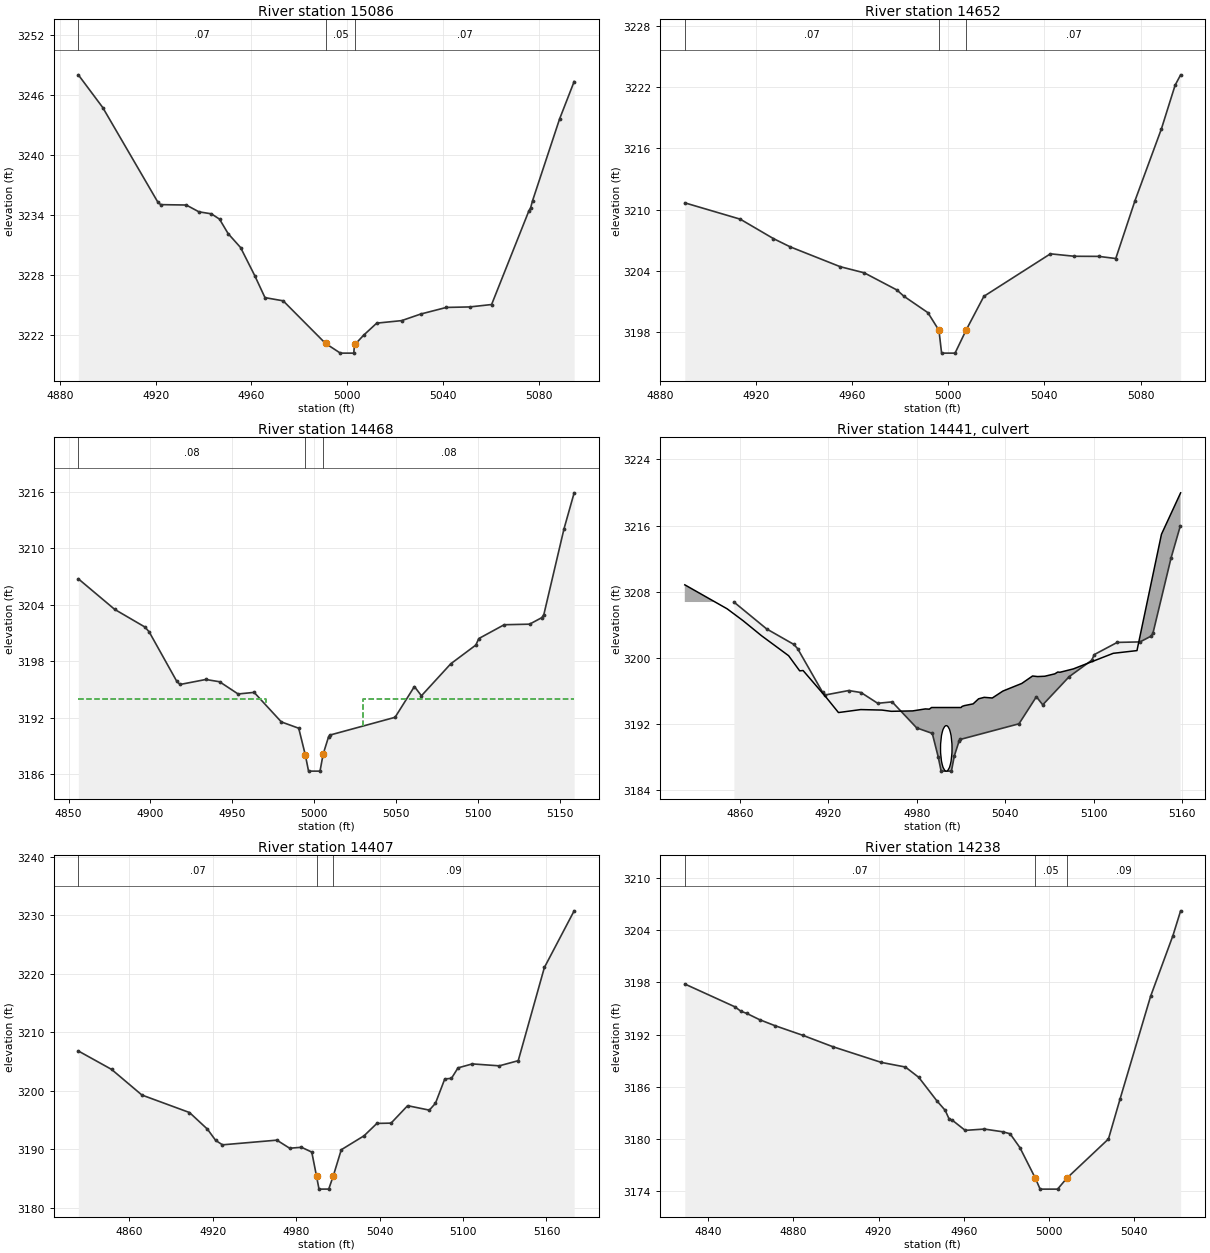
Type RM Length L Ch R = 1 ,15086   ,434,434,434
BEGIN DESCRIPTION:
XS1
END DESCRIPTION:
XS GIS Cut Line= 5
        794856.8       655524.39       794838.17       655467.35
       794838.17       655411.48       794834.68        655355.6
        794824.2       655321.84
#Sta/Elev= 30
  4887.7 3248.06  4897.9 3244.79  4920.9 3235.34  4922.1 3235.08  4932.8 3235.04
  4938.1 3234.36  4943.3 3234.16  4946.7 3233.63  4950.3 3232.18  4955.5 3230.79
  4961.4 3227.99  4965.7 3225.78  4973.3 3225.46    4991  3221.2  4997.2 3220.23
  5002.8 3220.23  5003.1 3221.04  5003.5 3221.15    5007 3222.04  5012.4 3223.23
  5022.8 3223.48  5030.8 3224.14  5041.5  3224.8  5051.3 3224.85  5060.4 3225.09
    5076 3234.47  5076.7 3234.75  5077.5 3235.46  5088.8 3243.64  5094.9 3247.39
#Mann= 3 ,-1 , 0
  4887.7     .07       0    4991     .05       0  5003.5     .07       0
Bank Sta=4991,5003.5
Exp/Cntr=0.3,0.1

Type RM Length L Ch R = 1 ,14652   ,184,184,184
BEGIN DESCRIPTION:
XS2
END DESCRIPTION:
XS GIS Cut Line= 4
       795213.02       655381.21       795237.46       655288.08
       795233.97       655257.81       795195.55       655187.97
#Sta/Elev= 22
  4890.3 3210.68  4913.4 3209.08  4927.2 3207.18  4934.2 3206.37    4955 3204.43
    4965 3203.83  4978.6 3202.15  4981.5 3201.54  4991.5 3199.93  4996.1  3198.2
  4997.2 3195.97  5002.8 3195.97  5007.4 3198.22  5014.8 3201.53  5042.5 3205.69
  5052.5 3205.45  5062.6 3205.44  5069.7 3205.23  5077.7 3210.89  5088.7 3217.92
  5094.4 3222.19  5096.7 3223.21
#Mann= 3 ,-1 , 0
  4890.3     .07       0  4996.1     .05       0  5007.4     .07       0
Bank Sta=4996.1,5007.4
Exp/Cntr=0.5,0.3

Type RM Length L Ch R = 1 ,14468   ,61,61,61
BEGIN DESCRIPTION:
XS2.3
END DESCRIPTION:
XS GIS Cut Line= 5
       795462.98       655268.36       795440.67       655210.35
       795366.72       655156.81       795294.05       655208.44
       795251.98       655165.73
#Sta/Elev= 30
    4856 3206.75  4878.2  3203.5  4896.6 3201.63  4899.2 3201.12  4916.1 3195.85
  4918.1 3195.52  4933.8 3196.05  4942.2 3195.81  4953.5 3194.51  4963.3 3194.68
  4979.9 3191.54  4990.5 3190.87  4994.5 3188.05  4996.5 3186.31  5003.5 3186.31
  5005.4 3188.11  5008.7 3189.95  5009.5 3190.14  5049.3 3192.03  5061.1  3195.3
  5065.4 3194.32  5083.3 3197.72  5098.6 3199.71  5100.4  3200.4  5115.9 3201.87
  5131.4 3201.93  5138.8 3202.62  5140.1 3202.95  5152.4 3212.06  5158.6 3215.89
#Mann= 3 ,-1 , 0
    4856     .08       0  4994.5     .05       0  5005.4     .08       0
#XS Ineff= 2 , 0
       0  4970.5    3194  5029.5       0    3194
Permanent Ineff=
       F       F
Bank Sta=4994.5,5005.4
Exp/Cntr=0.5,0.3

Type RM Length L Ch R = 2 ,14441   ,,,
BEGIN DESCRIPTION:
XS2.5 TOR
Structure ID: XS2.5
Approximate Survey Structure
END DESCRIPTION:
Bridge Culvert--1,0,-1,-1, 0
Deck Dist Width WeirC Skew NumUp NumDn MinLoCord MaxHiCord MaxSubmerge Is_Ogee
19.5,36,3,0, 36, 36, , , , 0, 1,1,,
  4822.7  4851.4  4862.1  4874.7  4893.1  4900.6  4902.9  4918.5  4926.9    4942
  4956.4  4962.7  4977.2  4985.8  4988.5    4990    5010  5010.8  5012.3  5018.2
  5021.9  5025.7  5031.2  5038.4  5051.2  5058.5  5061.9  5066.8  5073.6  5075.6
  5077.1  5086.2  5113.2  5129.3  5145.9  5158.9
 3208.83 3205.93 3204.51 3202.68 3200.26 3198.43 3198.47 3195.24 3193.39 3193.75
 3193.69 3193.54 3193.59 3193.83  3193.8    3194    3194 3194.14 3194.23 3194.44
 3195.05 3195.23 3195.15 3195.99 3196.91 3197.81 3197.74 3197.78 3198.07 3198.29
 3198.26 3198.67 3200.55 3200.88 3214.94 3219.95
    3161    3161    3161    3161    3161    3161    3161    3161    3161    3161
    3161    3161    3161    3161    3161    3161    3161    3161    3161    3161
    3161    3161    3161    3161    3161    3161    3161    3161    3161    3161
    3161    3161    3161    3161    3161    3161
  4822.7  4851.4  4862.1  4874.7  4893.1  4900.6  4902.9  4918.5  4926.9    4942
  4956.4  4962.7  4977.2  4985.8  4988.5    4990    5010  5010.8  5012.3  5018.2
  5021.9  5025.7  5031.2  5038.4  5051.2  5058.5  5061.9  5066.8  5073.6  5075.6
  5077.1  5086.2  5113.2  5129.3  5145.9  5158.9
 3208.83 3205.93 3204.51 3202.68 3200.26 3198.43 3198.47 3195.24 3193.39 3193.75
 3193.69 3193.54 3193.59 3193.83  3193.8    3194    3194 3194.14 3194.23 3194.44
 3195.05 3195.23 3195.15 3195.99 3196.91 3197.81 3197.74 3197.78 3198.07 3198.29
 3198.26 3198.67 3200.55 3200.88 3214.94 3219.95
    3161    3161    3161    3161    3161    3161    3161    3161    3161    3161
    3161    3161    3161    3161    3161    3161    3161    3161    3161    3161
    3161    3161    3161    3161    3161    3161    3161    3161    3161    3161
    3161    3161    3161    3161    3161    3161
BR Coef= 1 , 1 , 0 ,1.25, 0 ,,,0.8,0,2,0,
WSPro=,,,, 1 ,,,, 0 ,,,, 0 ,,,,-1 ,-1 ,-1 , 0 , 0 , 0 , 0 , 0
Culvert=3,5.5,7.79,36,0.027,0.5,1,34,1,3186.31,5000,3183.21,5000,Culvert #1  , 0 ,19.5
Culvert Bottom n=0.027
BC Design=,, 0 ,, 0 ,,,,,,
BC HTab HWMax=3215.89

Type RM Length L Ch R = 1 ,14407   ,169,169,169
BEGIN DESCRIPTION:
XS2.7
END DESCRIPTION:
XS GIS Cut Line= 6
       795496.12       655263.26       795490.39       655172.74
       795396.04       655107.72       795368.63       655109.64
       795297.88       655153.62       795264.31        655131.5
#Sta/Elev= 30
  4823.5 3206.81  4847.4 3203.66  4869.2 3199.28  4903.4 3196.29  4916.3 3193.45
  4922.2 3191.53  4927.1 3190.77  4966.2 3191.57  4975.4 3190.19  4983.9 3190.35
  4991.3 3189.53  4994.7 3185.43  4996.5  3183.2  5003.5 3183.21  5006.8 3185.49
  5012.5 3189.93  5028.9 3192.32  5038.1 3194.43  5048.3 3194.48  5060.2 3197.46
  5075.8  3196.7  5080.2 3197.87  5086.9 3202.03  5091.7 3202.13  5096.4 3203.92
  5106.7  3204.6  5126.1 3204.27  5139.7 3205.15  5158.5 3221.08  5179.9 3230.76
#Mann= 3 ,-1 , 0
  4823.5     .07       0  4994.7     .05       0  5006.8     .09       0
#XS Ineff= 2 , 0
       0  4963.5    3189  5036.5       0    3189
Permanent Ineff=
       F       F
Bank Sta=4994.7,5006.8
Exp/Cntr=0.5,0.3

Type RM Length L Ch R = 1 ,14238   ,381,381,381
BEGIN DESCRIPTION:
XS3
END DESCRIPTION:
XS GIS Cut Line= 5
       795550.78       655208.46       795581.37        655094.1
       795573.39       655055.54       795560.09       655023.62
       795544.13       654986.39
#Sta/Elev= 29
    4829 3197.82  4852.5  3195.2  4855.4 3194.68    4858 3194.45  4864.1 3193.72
  4871.2 3193.04  4884.4 3191.92  4898.5 3190.61  4921.3  3188.8  4932.6 3188.27
  4938.9 3187.08  4947.4 3184.38  4951.3 3183.29  4953.1 3182.32  4954.7 3182.14
  4960.7 3180.98  4969.7 3181.13  4978.3 3180.82  4981.8 3180.59  4986.4    3179
  4993.7 3175.46  4995.9 3174.22  5004.1 3174.22  5008.5 3175.49    5028 3179.99
  5033.5 3184.63  5047.8 3196.41  5058.3  3203.4  5061.9 3206.24
#Mann= 3 ,-1 , 0
    4829     .07       0  4993.7     .05       0  5008.5     .09       0
Bank Sta=4993.7,5008.5
Exp/Cntr=0.5,0.3

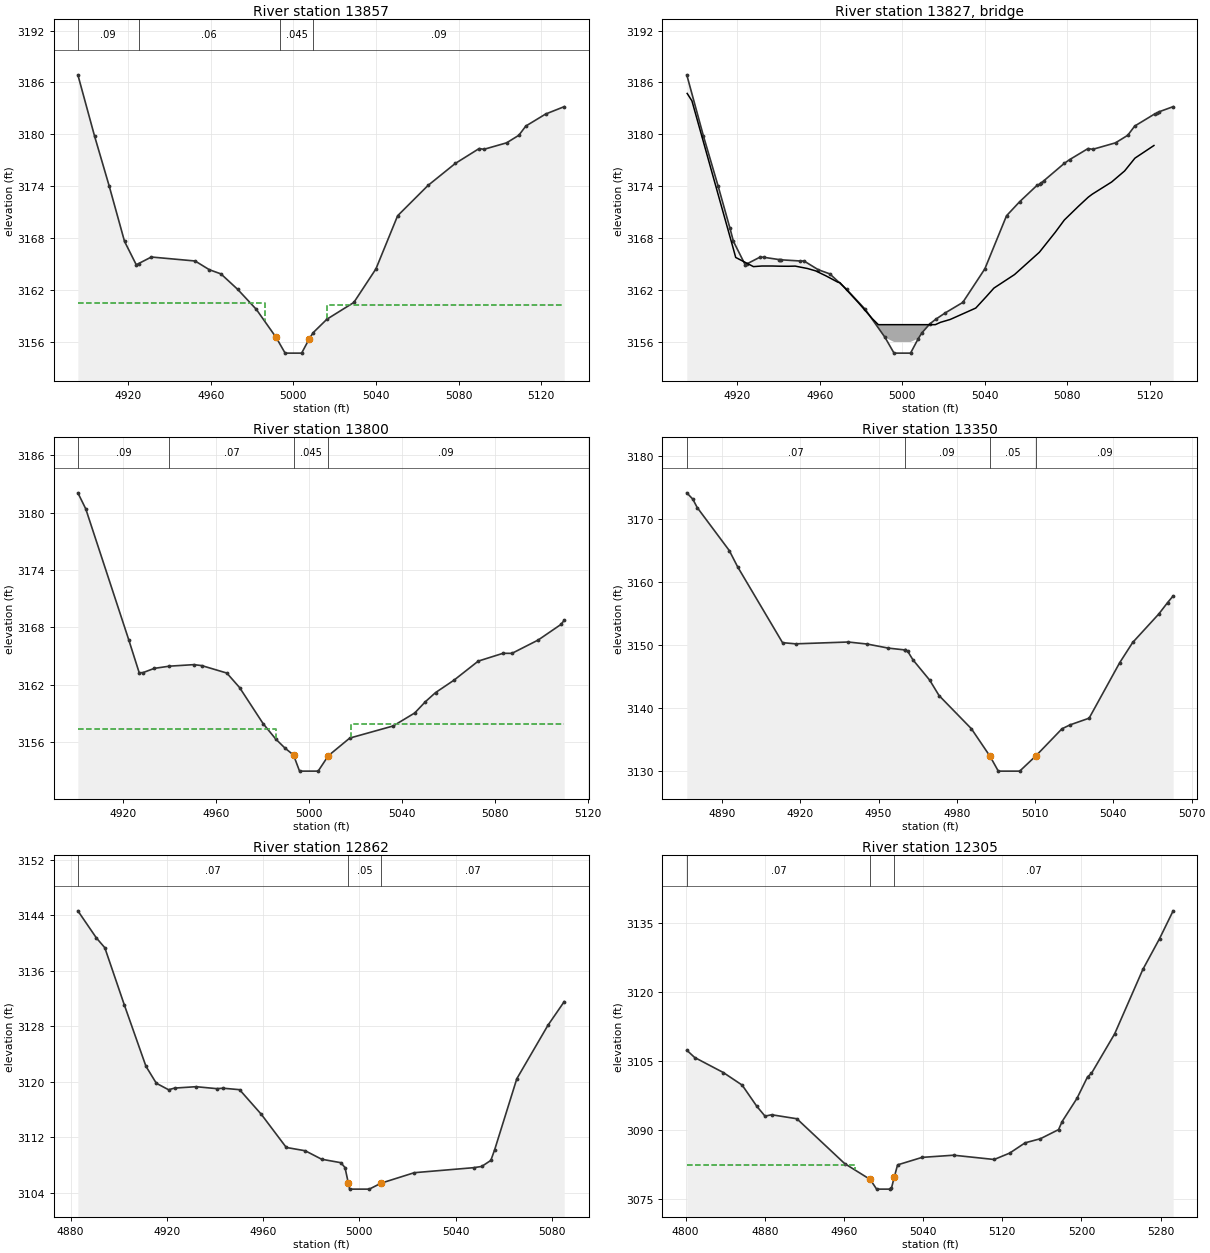
Type RM Length L Ch R = 1 ,13857   ,57,57,57
BEGIN DESCRIPTION:
XS3.7
END DESCRIPTION:
XS GIS Cut Line= 4
       795948.71       654968.12       795907.92        654918.4
       795890.07       654863.58       795903.45       654750.75
#Sta/Elev= 30
  4895.6 3186.88  4903.7 3179.79  4910.8 3174.01  4918.2 3167.63  4923.9 3164.92
    4925 3165.06  4931.2 3165.82  4952.4 3165.36  4959.3 3164.35  4964.9 3163.87
 4972.98 3162.09 4982.05 3159.77 4991.65 3156.52    4996 3154.71    5004 3154.71
 5007.77  3156.4  5009.6 3157.08 5016.24 3158.63  5029.3 3160.57 5039.99 3164.45
  5050.5 3170.59  5065.2 3174.09  5078.4 3176.63    5090 3178.36  5092.3 3178.27
  5103.3 3179.02  5109.2 3179.89  5112.6 3180.96  5122.2 3182.35  5131.2  3183.2
#Mann= 4 ,-1 , 0
  4895.6     .09       0    4925     .06       0 4993.43    .045       0
  5009.6     .09       0
#XS Ineff= 2 , 0
       0 4986.01 3160.53 5016.43       0 3160.23
Permanent Ineff=
       F       F
Bank Sta=4991.65,5007.77
Exp/Cntr=0.5,0.3

Type RM Length L Ch R = 3 ,13827   ,,,
BEGIN DESCRIPTION:
XS4 TOR
Structure ID: XS4
Approximate Survey Structure
END DESCRIPTION:
Bridge Culvert--1,0,-1,-1, 0
Deck Dist Width WeirC Skew NumUp NumDn MinLoCord MaxHiCord MaxSubmerge Is_Ogee
20,20,3,0, 42, 42, , , , 0, 1,1,,
  4895.8  4898.1    4918  4919.3  4927.9    4932    4937  4940.3  4944.8  4948.1
  4954.1    4958  4962.7    4964  4968.7  4969.8  4978.7  4985.4  4988.4    4990
    4990    5010    5010    5016  5018.5  5023.2  5035.6  5040.8  5044.4  5054.3
  5054.5  5054.6  5066.4  5074.1  5078.5  5085.4  5090.1    5092  5101.4  5107.7
  5112.7  5121.9
 3184.73 3183.87 3166.91 3165.77 3164.71 3164.78 3164.78 3164.76 3164.75 3164.77
 3164.49 3164.22 3163.68 3163.52 3162.92 3162.86 3160.55 3158.71    3158    3158
    3158    3158    3158    3158 3158.27  3158.6 3159.92 3161.27 3162.23 3163.78
 3163.82 3163.84 3166.37 3168.68  3170.1  3171.7 3172.74 3173.08 3174.49 3175.77
 3177.25 3178.71
    3134    3134    3134    3134    3134    3134    3134    3134    3134    3134
    3134    3134    3134    3134    3134    3134    3134    3134    3134    3134
    3156    3156    3136    3136    3134    3134    3134    3134    3134    3134
    3134    3134    3134    3134    3134    3134    3134    3134    3134    3134
    3134    3134
  4895.8  4898.1    4918  4919.3  4927.9    4932    4937  4940.3  4944.8  4948.1
  4954.1    4958  4962.7    4964  4968.7  4969.8  4978.7  4985.4  4988.4    4990
    4990    5010    5010    5016  5018.5  5023.2  5035.6  5040.8  5044.4  5054.3
  5054.5  5054.6  5066.4  5074.1  5078.5  5085.4  5090.1    5092  5101.4  5107.7
  5112.7  5121.9
 3184.73 3183.87 3166.91 3165.77 3164.71 3164.78 3164.78 3164.76 3164.75 3164.77
 3164.49 3164.22 3163.68 3163.52 3162.92 3162.86 3160.55 3158.71    3158    3158
    3158    3158    3158    3158 3158.27  3158.6 3159.92 3161.27 3162.23 3163.78
 3163.82 3163.84 3166.37 3168.68  3170.1  3171.7 3172.74 3173.08 3174.49 3175.77
 3177.25 3178.71
    3134    3134    3134    3134    3134    3134    3134    3134    3134    3134
    3134    3134    3134    3134    3134    3134    3134    3134    3134    3134
    3156    3156    3134    3134    3134    3134    3134    3134    3134    3134
    3134    3134    3134    3134    3134    3134    3134    3134    3134    3134
    3134    3134
BR Coef= 1 , 1 , 0 ,1.25, 0 ,,,0.8,0,2,0,
WSPro=,,,, 1 ,,,, 0 ,,,, 0 ,,,,-1 ,-1 ,-1 , 0 , 0 , 0 , 0 , 0
BR U #Sta/Elev= 45
  4895.6 3186.88  4903.7 3179.79  4910.8 3174.01  4916.5 3169.17  4918.2 3167.63
  4923.9 3164.92    4925 3165.06  4931.2 3165.82  4932.8 3165.79  4940.2 3165.53
  4940.9  3165.5  4941.1  3165.5  4950.6 3165.36  4952.4 3165.36  4959.3 3164.35
  4964.9 3163.87 4972.98 3162.09 4982.05 3159.77 4991.65 3156.52    4996 3154.71
    5004 3154.71 5007.77  3156.4  5009.6 3157.08 5013.39  3158.1 5016.24 3158.63
 5020.81 3159.36  5029.3 3160.57 5039.99 3164.45  5050.5 3170.59  5056.8  3172.2
  5065.2 3174.09  5066.9 3174.29  5067.3 3174.38  5068.5 3174.62  5078.4 3176.63
    5081 3177.07    5090 3178.36  5092.3 3178.27  5103.3 3179.02  5109.2 3179.89
  5112.6 3180.96  5122.2 3182.35  5123.4 3182.41  5124.3  3182.6  5131.2  3183.2
BR U #Mann= 4
  4895.6     .09    4925     .06    4996     .04  5009.6     .09
BR D #Sta/Elev= 38
  4900.6 3182.07    4904 3180.39  4922.5 3166.68    4927 3163.23  4928.7 3163.25
  4933.5 3163.69  4935.2 3163.74    4940 3163.92    4941 3163.96  4944.1 3163.96
  4950.5 3164.08  4953.9 3163.98  4960.7 3163.44  4963.8 3163.25  4964.7  3163.2
  4970.2 3161.68 4980.36 3157.89 4985.79 3156.28 4989.78 3155.33  4993.4 3154.62
    4996 3152.93    5004 3152.93 5008.38 3154.54  5017.6 3156.39  5025.4 3156.87
  5036.3 3157.66 5045.57 3159.02 5050.16  3160.2 5054.51 3161.15  5061.9  3162.4
  5062.5 3162.46  5072.9 3164.45  5083.6 3165.27  5087.4 3165.26  5097.9 3166.55
  5098.7 3166.66  5108.5 3168.29  5109.9 3168.73
BR D #Mann= 4
  4900.6     .09    4940     .07  4993.4     .04 5008.38     .09
BC Design=,, 0 ,, 0 ,,,,,,
BC HTab HWMax=3186.88

Type RM Length L Ch R = 1 ,13800   ,450,450,450
BEGIN DESCRIPTION:
XS4.2
END DESCRIPTION:
XS GIS Cut Line= 4
       795990.15       654947.09       795968.47       654911.39
       795946.16       654868.68       795964.65       654750.75
#Sta/Elev= 30
  4900.6 3182.07    4904 3180.39  4922.5 3166.68    4927 3163.23  4928.7 3163.25
  4933.5 3163.69    4940 3163.92  4950.5 3164.08  4953.9 3163.98  4964.7  3163.2
  4970.2 3161.68 4980.36 3157.89 4985.79 3156.28 4989.78 3155.33  4993.4 3154.62
    4996 3152.93    5004 3152.93 5008.38 3154.54  5017.6 3156.39  5036.3 3157.66
 5045.57 3159.02 5050.16  3160.2 5054.51 3161.15  5062.5 3162.46  5072.9 3164.45
  5083.6 3165.27  5087.4 3165.26  5098.7 3166.66  5108.5 3168.29  5109.9 3168.73
#Mann= 4 ,-1 , 0
  4900.6     .09       0    4940     .07       0  4993.4    .045       0
 5008.38     .09       0
#XS Ineff= 2 , 0
       0 4985.86 3157.37    5018       0 3157.87
Permanent Ineff=
       F       F
Bank Sta=4993.4,5008.38
Exp/Cntr=0.5,0.3

Type RM Length L Ch R = 1 ,13350   ,488,488,488
BEGIN DESCRIPTION:
XS5
END DESCRIPTION:
XS GIS Cut Line= 5
        796400.5       654703.15       796388.53       654663.26
       796328.69       654630.02       796294.12       654615.39
       796256.88       654604.75
#Sta/Elev= 29
  4876.5 3174.13  4878.8 3173.14  4880.5  3171.8  4892.8 3164.98    4896  3162.4
  4913.2 3150.39  4918.2  3150.2  4938.4 3150.49  4945.6 3150.17  4953.8 3149.52
    4960 3149.24  4960.3 3149.23  4961.2    3149  4963.2 3147.66  4969.6 3144.45
  4973.2    3142  4985.6 3136.74  4992.7  3132.4  4995.9 3130.03  5004.1 3130.03
  5010.3 3132.45  5020.3 3136.74  5023.4 3137.36  5030.7 3138.42  5042.4  3147.2
  5047.4 3150.42  5057.4 3154.93  5060.8 3156.75  5062.9 3157.79
#Mann= 4 ,-1 , 0
  4876.5     .07       0    4960     .09       0  4992.7     .05       0
  5010.3     .09       0
Bank Sta=4992.7,5010.3
Exp/Cntr=0.3,0.1

Type RM Length L Ch R = 1 ,12862   ,557,557,557
BEGIN DESCRIPTION:
XS6
END DESCRIPTION:
XS GIS Cut Line= 4
       796606.61       654310.87       796565.39       654260.34
       796550.76       654223.11       796484.27       654152.63
#Sta/Elev= 30
    4883 3144.64  4890.7 3140.73  4894.2 3139.32  4902.3 3131.08  4911.3 3122.22
  4915.6 3119.78  4920.7 3118.84  4923.2 3119.08  4932.1 3119.28  4940.7    3119
  4943.4 3119.06  4950.2 3118.85  4959.2 3115.31  4969.6 3110.52  4977.5 3110.04
  4984.3 3108.82  4992.3 3108.32    4994 3107.62  4995.4 3105.37  4995.9 3104.51
  5004.1 3104.51    5009 3105.37  5022.8 3106.88  5047.4  3107.6  5050.8 3107.78
  5054.6 3108.65  5056.2  3110.2  5065.4 3120.43  5078.3 3128.12  5085.1 3131.55
#Mann= 3 ,-1 , 0
    4883     .07       0  4995.4     .05       0    5009     .07       0
#Block Obstruct= 1 ,-1
    4990    4960    3125
Bank Sta=4995.4,5009
Exp/Cntr=0.3,0.1

Type RM Length L Ch R = 1 ,12305   ,58,58,58
BEGIN DESCRIPTION:
XS7
END DESCRIPTION:
XS GIS Cut Line= 6
       796942.63       653827.74       796894.68       653797.85
       796848.81       653767.97         796739.       653737.39
       796609.73       653720.71       796476.29        653694.3
#Sta/Elev= 30
  4801.1 3107.39  4809.1  3105.8    4838 3102.54  4857.1  3099.8  4871.9  3095.2
  4880.2 3093.06  4886.9 3093.36  4912.4 3092.49  4960.7 3082.75  4986.5  3079.3
    4993  3077.2    5007  3077.2    5008  3077.4 5010.79 3079.79  5014.2 3082.47
    5039  3084.1  5070.8 3084.57  5111.8 3083.64  5127.5 3085.03  5143.1 3087.26
  5158.5 3088.15  5176.9 3090.13  5180.5 3091.89  5195.5 3096.92  5206.2  3101.6
  5210.1 3102.34  5233.6 3110.94  5262.1 3124.94    5279 3131.64  5292.7 3137.67
#Mann= 3 , 0 , 0
  4801.1     .07       0  4986.5     .05       0 5010.79     .07       0
#XS Ineff= 2 , 0
       0    4971 3082.48    5029       0 3082.64
Permanent Ineff=
       F       F
Bank Sta=4986.5,5010.79
Exp/Cntr=0.5,0.3

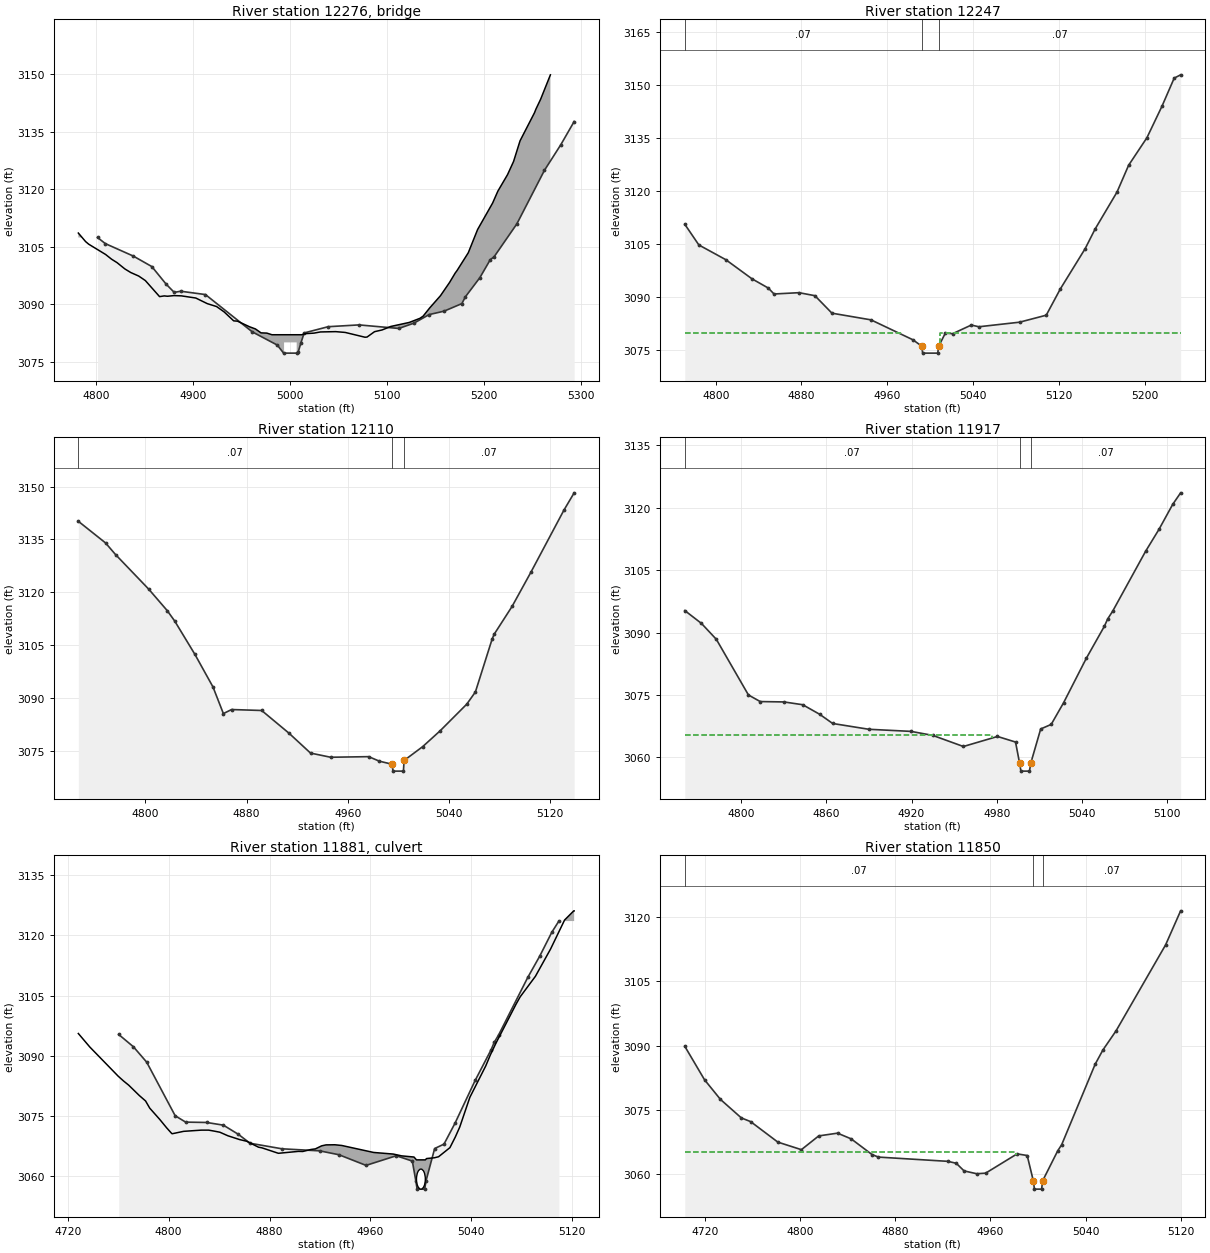
Type RM Length L Ch R = 3 ,12276   ,,,
BEGIN DESCRIPTION:
z1tor
Structure ID: 2991 plot creek rd
Approximate Survey Structure
END DESCRIPTION:
Bridge Culvert--1,0,-1,-1, 0
Deck Dist Width WeirC Skew NumUp NumDn MinLoCord MaxHiCord MaxSubmerge Is_Ogee
22.5,13,3,0, 60, 60, , , , 0, 1,1,,
  4781.3  4788.8    4792  4809.4  4815.6  4821.2  4829.3  4835.4  4843.6  4850.4
  4865.1  4869.9  4873.3  4879.9  4887.6  4902.4  4914.3  4923.9  4931.7  4941.5
  4945.5  4957.9    4964  4969.7  4975.7    4981  4993.5  4993.5  5006.5  5006.5
  5011.8  5015.6  5024.3    5031  5046.8  5056.6    5077  5079.1  5086.8  5094.6
  5103.5  5122.6  5133.6  5136.9  5143.8  5154.8  5164.2    5170  5171.9  5183.5
  5193.1  5208.6    5214    5224  5230.2  5236.9  5251.8  5253.2  5258.1  5268.2
 3108.55 3106.32 3105.64 3102.96 3101.72 3100.83 3099.18 3098.24 3097.32 3096.15
 3091.95 3092.14 3092.05 3092.22 3092.15 3091.59 3090.12 3089.36 3087.96 3085.63
 3085.54 3084.08 3083.51 3082.49 3082.43    3082    3082    3082    3082    3082
    3082 3082.29 3082.42 3082.73 3082.81  3082.6 3081.35  3081.4  3082.8 3083.25
 3084.16 3085.21 3086.28 3086.85 3089.03 3092.19 3095.66 3098.11 3098.76 3103.41
 3109.47 3116.39 3119.49 3123.81 3127.24 3132.64 3139.97 3140.87 3143.48 3149.86
 3054.21 3054.21 3054.21 3054.21 3054.21 3054.21 3054.21 3054.21 3054.21 3054.21
 3054.21 3054.21 3054.21 3054.21 3054.21 3054.21 3054.21 3054.21 3054.21 3054.21
 3054.21 3054.21 3054.21 3054.21 3054.21 3054.21 3054.21    3080    3080 3054.21
 3054.21 3054.21 3054.21 3054.21 3054.21 3054.21 3054.21 3054.21 3054.21 3054.21
 3054.21 3054.21 3054.21 3054.21 3054.21 3054.21 3054.21 3054.21 3054.21 3054.21
 3054.21 3054.21 3054.21 3054.21 3054.21 3054.21 3054.21 3054.21 3054.21 3054.21
  4781.3  4788.8    4792  4809.4  4815.6  4821.2  4829.3  4835.4  4843.6  4850.4
  4865.1  4869.9  4873.3  4879.9  4887.6  4902.4  4914.3  4923.9  4931.7  4941.5
  4945.5  4957.9    4964  4969.7  4975.7    4981  4993.5  4993.5  5006.5  5006.5
  5011.8  5015.6  5024.3    5031  5046.8  5056.6    5077  5079.1  5086.8  5094.6
  5103.5  5122.6  5133.6  5136.9  5143.8  5154.8  5164.2    5170  5171.9  5183.5
  5193.1  5208.6    5214    5224  5230.2  5236.9  5251.8  5253.2  5258.1  5268.2
 3108.55 3106.32 3105.64 3102.96 3101.72 3100.83 3099.18 3098.24 3097.32 3096.15
 3091.95 3092.14 3092.05 3092.22 3092.15 3091.59 3090.12 3089.36 3087.96 3085.63
 3085.54 3084.08 3083.51 3082.49 3082.43    3082    3082    3082    3082    3082
    3082 3082.29 3082.42 3082.73 3082.81  3082.6 3081.35  3081.4  3082.8 3083.25
 3084.16 3085.21 3086.28 3086.85 3089.03 3092.19 3095.66 3098.11 3098.76 3103.41
 3109.47 3116.39 3119.49 3123.81 3127.24 3132.64 3139.97 3140.87 3143.48 3149.86
 3054.21 3054.21 3054.21 3054.21 3054.21 3054.21 3054.21 3054.21 3054.21 3054.21
 3054.21 3054.21 3054.21 3054.21 3054.21 3054.21 3054.21 3054.21 3054.21 3054.21
 3054.21 3054.21 3054.21 3054.21 3054.21 3054.21 3054.21    3080    3080 3054.21
 3054.21 3054.21 3054.21 3054.21 3054.21 3054.21 3054.21 3054.21 3054.21 3054.21
 3054.21 3054.21 3054.21 3054.21 3054.21 3054.21 3054.21 3054.21 3054.21 3054.21
 3054.21 3054.21 3054.21 3054.21 3054.21 3054.21 3054.21 3054.21 3054.21 3054.21
Abutment Skew #Up #Dn= , 2 , 2
  4993.5  4994.5
    3080  3077.2
  4993.5  4994.5
    3080 3076.95
Abutment Skew #Up #Dn= , 2 , 2
  5005.5  5006.5
  3077.2    3080
  5005.5  5006.5
 3076.95    3080
BR Coef= 1 , 1 , 0 ,1.25, 0 ,,,0.8,0,2,0,
WSPro=,,,, 1 ,,,, 0 ,,,, 0 ,,,,-1 ,-1 ,-1 , 0 , 0 , 0 , 0 , 0
BC Design=,, 0 ,, 0 ,,,,,,
BC HTab HWMax=3137.67

Type RM Length L Ch R = 1 ,12247   ,137,137,137
BEGIN DESCRIPTION:
z2
END DESCRIPTION:
XS GIS Cut Line= 5
       796977.38        653777.7       796861.32       653722.79
       796769.58       653686.65       796671.58       653667.19
        796543.7       653622.71
#Sta/Elev= 30
  4771.2 3110.66  4784.3 3104.81  4809.4 3100.65  4833.8 3095.24  4849.1 3092.61
  4854.4 3090.94  4877.7 3091.31  4892.5 3090.46  4908.4 3085.51  4944.8 3083.62
  4983.8    3078    4992 3076.21    4993 3074.21    5007 3074.21    5008 3076.21
  5014.1 3079.86    5021 3079.72  5038.3 3082.15  5045.4 3081.67  5083.3 3082.96
  5108.2 3084.94  5121.3 3092.35  5144.5 3103.77  5153.7 3109.28  5174.2 3119.78
    5185 3127.35  5202.1 3135.16  5216.1 3144.05  5227.5 3152.01  5233.5 3152.94
#Mann= 3 ,-1 , 0
  4771.2     .07       0    4992     .05       0    5008     .07       0
#XS Ineff= 2 , 0
       0    4974    3080    5009       0    3080
Permanent Ineff=
       F       F
Bank Sta=4992,5008
Exp/Cntr=0.5,0.3

Type RM Length L Ch R = 1 ,12110   ,193,193,193
BEGIN DESCRIPTION:
z5
END DESCRIPTION:
XS GIS Cut Line= 4
        797030.7       653660.77       796925.61       653603.45
       796813.58       653560.03       796671.15       653506.19
#Sta/Elev= 30
    4747 3140.15  4768.5 3134.01  4776.4 3130.71  4802.7 3120.86  4817.3 3114.78
  4823.2 3111.83  4839.2 3102.35  4853.5 3093.09  4861.7 3085.54  4868.2 3086.69
    4892 3086.42  4913.6 3079.97  4930.6 3074.33  4946.5 3073.14  4976.6 3073.31
  4985.1 3072.02    4995 3071.17  4995.9  3069.2  5004.1  3069.2  5004.6 3072.22
  5019.3 3076.15    5033 3080.61  5054.2 3088.23    5061 3091.68  5074.2 3106.66
  5075.8 3108.05    5090 3115.97  5104.9 3125.69    5131 3143.31  5139.1 3148.23
#Mann= 3 , 0 , 0
    4747     .07       0    4995     .05       0  5004.6     .07       0
Bank Sta=4995,5004.6
Exp/Cntr=0.5,0.3

Type RM Length L Ch R = 1 ,11917   ,67,67,67
BEGIN DESCRIPTION:
XS8
END DESCRIPTION:
XS GIS Cut Line= 5
       797055.88       653460.16       796991.21       653410.65
       796834.22       653365.39       796794.38       653353.44
       796734.55        653335.1
#Sta/Elev= 30
  4760.4 3095.29  4772.1 3092.21  4782.6 3088.38  4805.2    3075  4813.5 3073.42
  4830.2 3073.33  4843.4 3072.66  4855.3 3070.37  4864.5 3068.15  4889.9 3066.76
  4919.7 3066.25    4935 3065.28  4956.5 3062.62  4980.5 3065.03  4993.2 3063.69
    4996  3058.7    4997  3056.7    5003  3056.7    5004  3058.7  5010.9 3066.83
  5018.3 3067.93    5027 3073.12    5043 3083.81  5055.7  3091.5  5058.1 3093.31
  5061.6 3095.16  5084.7 3109.51  5094.2 3114.83  5103.8  3120.8  5109.4 3123.59
#Mann= 3 ,-1 , 0
  4760.4     .07       0    4996     .05       0    5004     .07       0
#XS Ineff= 2 , 0
       0  4976.5 3065.49  5023.5       0 3067.36
Permanent Ineff=
       F       F
Bank Sta=4996,5004
Exp/Cntr=0.5,0.3

Type RM Length L Ch R = 2 ,11881   ,,,
BEGIN DESCRIPTION:
z3-tor_culvert
Structure ID: old road bed
Approximate Survey Structure
END DESCRIPTION:
Bridge Culvert--1,0,-1,-1, 0
Deck Dist Width WeirC Skew NumUp NumDn MinLoCord MaxHiCord MaxSubmerge Is_Ogee
20,32,3,0, 54, 54, , , , 0, 1,1,,
  4728.4  4737.5    4760  4764.4  4768.3  4776.8  4781.7    4785  4792.9  4798.4
  4802.5    4803  4811.9  4825.9  4831.7  4835.7  4840.6    4847  4856.2  4861.9
  4871.2    4874    4887  4902.9  4906.3  4912.8  4916.3  4921.3  4924.8  4931.8
  4937.3  4962.5  4978.1  4984.7  4994.5  4996.5  5003.5  5004.5  5010.8    5014
    5023  5027.3  5030.8  5038.8  5051.4  5055.1  5059.5  5075.5  5078.7  5090.8
  5102.8  5113.9  5121.2  5121.5
 3095.53 3092.16 3084.88 3083.64 3082.65 3080.04  3078.7 3076.91 3074.11    3072
 3070.56 3070.53 3071.12 3071.42 3071.42  3071.2  3070.9 3070.01 3069.07 3068.64
 3067.17    3067 3065.64 3066.12 3066.09 3066.59 3066.74  3067.5 3067.74 3067.77
 3067.59 3065.85 3065.45    3065 3064.71    3064    3064 3064.33 3064.53 3064.78
 3067.05 3069.72  3072.2  3079.6 3087.44 3090.22 3093.13 3102.89 3104.68 3109.81
 3116.61 3123.84 3126.14 3126.13
  3036.7  3036.7  3036.7  3036.7  3036.7  3036.7  3036.7  3036.7  3036.7  3036.7
  3036.7  3036.7  3036.7  3036.7  3036.7  3036.7  3036.7  3036.7  3036.7  3036.7
  3036.7  3036.7  3036.7  3036.7  3036.7  3036.7  3036.7  3036.7  3036.7  3036.7
  3036.7  3036.7  3036.7  3036.7  3036.7  3036.7  3036.7  3036.7  3036.7  3036.7
  3036.7  3036.7  3036.7  3036.7  3036.7  3036.7  3036.7  3036.7  3036.7  3036.7
  3036.7  3036.7  3036.7  3036.7
  4728.4  4737.5    4760  4764.4  4768.3  4776.8  4781.7    4785  4792.9  4798.4
  4802.5    4803  4811.9  4825.9  4831.7  4835.7  4840.6    4847  4856.2  4861.9
  4871.2    4874    4887  4902.9  4906.3  4912.8  4916.3  4921.3  4924.8  4931.8
  4937.3  4962.5  4978.1  4984.7  4994.5  4996.5  5003.5  5004.5  5010.8    5014
    5023  5027.3  5030.8  5038.8  5051.4  5055.1  5059.5  5075.5  5078.7  5090.8
  5102.8  5113.9  5121.2  5121.5
 3095.53 3092.16 3084.88 3083.64 3082.65 3080.04  3078.7 3076.91 3074.11    3072
 3070.56 3070.53 3071.12 3071.42 3071.42  3071.2  3070.9 3070.01 3069.07 3068.64
 3067.17    3067 3065.64 3066.12 3066.09 3066.59 3066.74  3067.5 3067.74 3067.77
 3067.59 3065.85 3065.45    3065 3064.71    3064    3064 3064.33 3064.53 3064.78
 3067.05 3069.72  3072.2  3079.6 3087.44 3090.22 3093.13 3102.89 3104.68 3109.81
 3116.61 3123.84 3126.14 3126.13
 3036.54 3036.54 3036.54 3036.54 3036.54 3036.54 3036.54 3036.54 3036.54 3036.54
 3036.54 3036.54 3036.54 3036.54 3036.54 3036.54 3036.54 3036.54 3036.54 3036.54
 3036.54 3036.54 3036.54 3036.54 3036.54 3036.54 3036.54 3036.54 3036.54 3036.54
 3036.54 3036.54 3036.54 3036.54 3036.54 3036.54 3036.54 3036.54 3036.54 3036.54
 3036.54 3036.54 3036.54 3036.54 3036.54 3036.54 3036.54 3036.54 3036.54 3036.54
 3036.54 3036.54 3036.54 3036.54
Culvert=5,5,7,32,0.027,0.5,1,41,1,3056.7,5000,3056.54,5000,Culvert #1  , 0 ,20
Culvert Bottom n=0.027
BC Design=,, 0 ,, 0 ,,,,,,
BC HTab HWMax=3123.59

Type RM Length L Ch R = 1 ,11850   ,145,145,145
BEGIN DESCRIPTION:
z4
END DESCRIPTION:
XS GIS Cut Line= 5
       797147.94       653392.42       797066.31       653355.07
        796934.3       653322.94       796867.43       653306.44
       796749.31       653273.44
#Sta/Elev= 30
  4702.8 3089.84  4719.4 3082.04  4732.8 3077.46  4750.4 3073.14  4758.2 3072.28
  4781.1  3067.5  4800.9 3065.74  4815.5 3068.95  4831.3 3069.59  4842.8 3068.26
  4860.3 3064.61  4865.7 3064.01  4924.1 3063.02  4931.2 3062.57  4937.8 3060.79
  4948.4 3060.13  4955.9 3060.26  4982.4 3064.76  4990.9 3064.38    4996 3058.54
    4997 3056.54    5003 3056.54    5004 3058.54  5016.6 3065.48  5019.9 3066.89
  5048.1 3085.67  5054.6 3088.98  5065.7 3093.46  5107.4 3113.51    5120 3121.43
#Mann= 3 ,-1 , 0
  4702.8     .07       0    4996     .05       0    5004     .07       0
#XS Ineff= 2 , 0
       0  4981.5 3065.22  5018.5       0 3065.92
Permanent Ineff=
       F       F
Bank Sta=4996,5004
Exp/Cntr=0.5,0.3