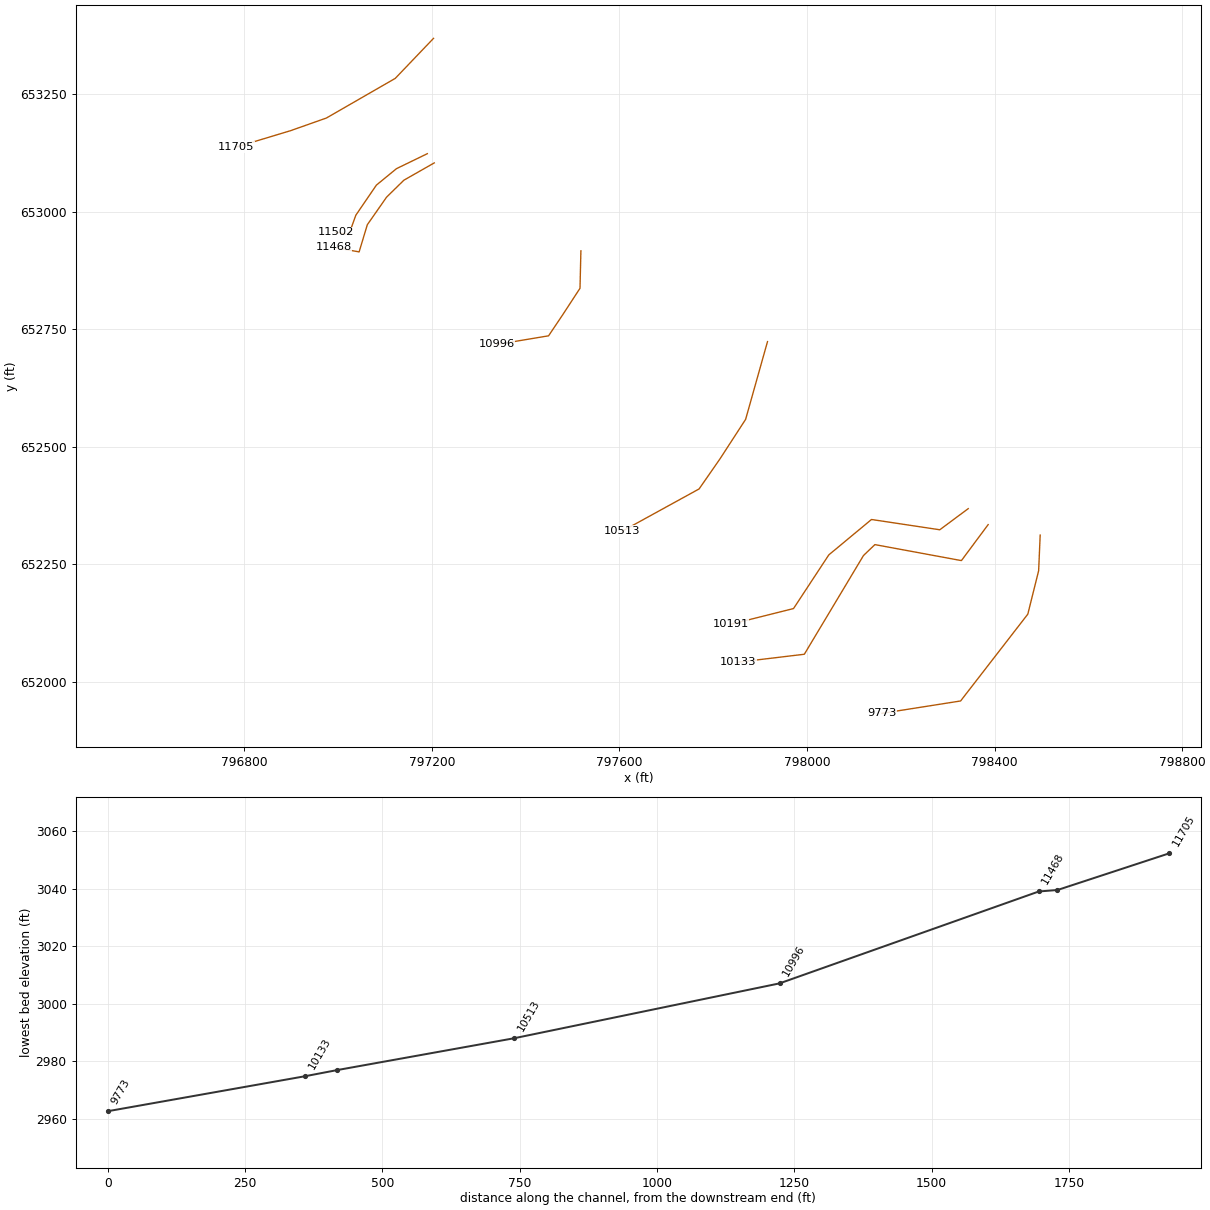
HEC-RAS study lds_plott_crk.prj: Plott Creek Limited Detail Study

--- lds_plott_crk.g01 (geometry) --- (continued)

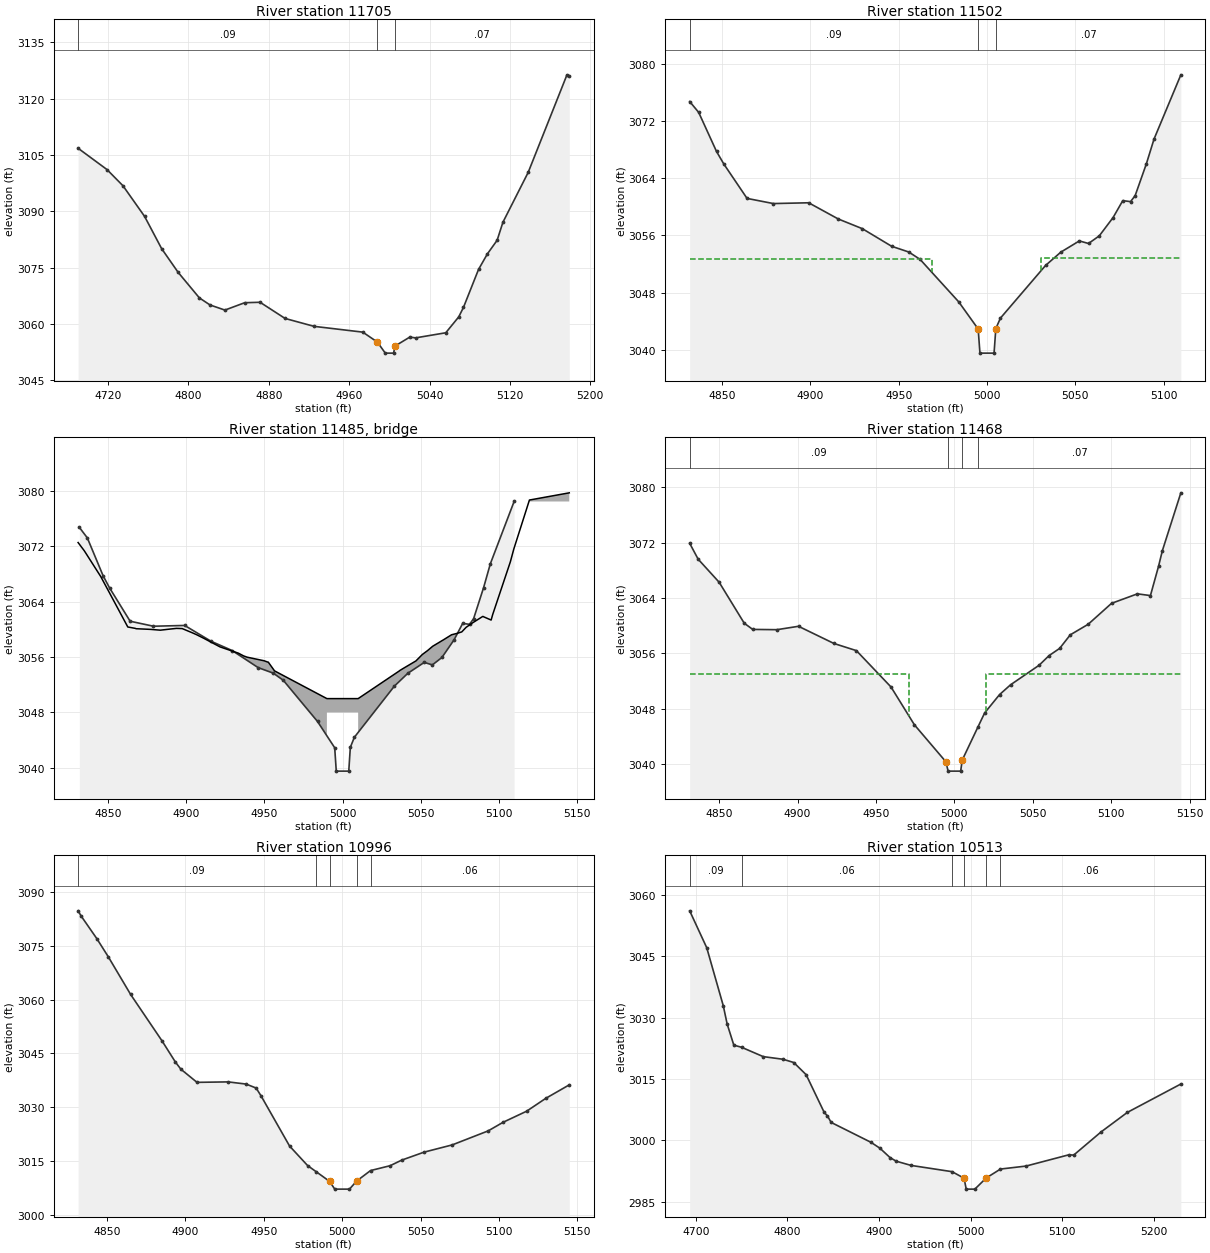
Type RM Length L Ch R = 1 ,11705   ,203,203,203
BEGIN DESCRIPTION:
z6
END DESCRIPTION:
XS GIS Cut Line= 5
       797203.52        653368.1       797121.89       653282.99
       796975.12       653198.75       796898.69       653171.83
       796783.18       653137.09
#Sta/Elev= 30
  4690.2 3106.79    4719 3101.11  4734.9 3096.79  4756.4 3088.64  4773.3 3080.08
  4789.8 3073.74  4810.9 3066.95  4821.5 3065.07  4836.3 3063.71    4856 3065.67
  4871.3 3065.79  4896.2 3061.48    4925 3059.38  4973.5 3057.84    4988  3055.2
  4995.9 3052.25  5004.1 3052.25  5005.8 3054.17  5020.3 3056.52    5026 3056.31
  5056.1 3057.67    5069  3061.9  5073.7 3064.42  5088.7 3074.53  5097.5 3078.66
  5107.2 3082.29    5113 3087.11  5138.1 3100.36  5176.7 3126.34    5179 3126.06
#Mann= 3 , 0 , 0
  4690.2     .09       0    4988     .05       0  5005.8     .07       0
Bank Sta=4988,5005.8
Exp/Cntr=0.5,0.3

Type RM Length L Ch R = 1 ,11502   ,34,34,34
BEGIN DESCRIPTION:
XS8.7
END DESCRIPTION:
XS GIS Cut Line= 6
        797190.2        653122.9       797124.48       653091.07
       797081.56       653056.03       797037.76       652992.09
       797022.87       652950.92       796994.84       652956.17
#Sta/Elev= 30
  4831.6  3074.7  4836.7 3073.18  4846.8 3067.72  4850.9 3065.98  4864.1 3061.16
    4879 3060.44    4899 3060.55  4915.8 3058.28  4929.4 3056.93    4946 3054.47
  4955.7 3053.67  4962.1 3052.64    4984  3046.7    4995 3042.91    4996 3039.54
    5004 3039.54    5005 3042.97  5007.6 3044.43  5033.2  3051.8  5041.8 3053.65
  5052.3 3055.22  5057.5 3054.86  5063.6 3055.93  5071.4 3058.48  5076.9 3060.85
  5081.3 3060.71  5083.9 3061.54  5090.3 3066.02  5094.6 3069.45  5109.8 3078.43
#Mann= 3 ,-1 , 0
  4831.6     .09       0    4995    .048       0    5005     .07       0
#XS Ineff= 2 , 0
       0 4968.64  3052.7  5030.6       0 3052.78
Permanent Ineff=
       F       F
Bank Sta=4995,5005
Exp/Cntr=0.5,0.3

Type RM Length L Ch R = 3 ,11485   ,,,
BEGIN DESCRIPTION:
XS9 TOR
Structure ID: 1834
Approximate Survey Structure
END DESCRIPTION:
Bridge Culvert--1,0,-1,-1, 0
Deck Dist Width WeirC Skew NumUp NumDn MinLoCord MaxHiCord MaxSubmerge Is_Ogee
10.5,13,3,0, 53, 53, , , , 0, 1,1,,
  4830.8  4834.8  4845.3  4862.6  4867.4  4867.9  4877.5    4879  4883.4  4890.5
    4893  4893.7  4897.4  4903.8  4906.7  4911.4  4911.7  4911.8  4921.6  4933.4
  4936.7  4938.9  4949.8    4952  4952.5  4955.8  4956.5    4990    4990    5010
    5010  5036.4  5036.6  5036.7  5039.2    5047  5051.1  5054.5  5057.7  5064.8
  5069.8  5073.5  5076.3  5079.1  5083.1  5089.8  5090.3  5095.1  5096.1  5107.4
  5109.6  5119.6  5145.1
 3072.51 3071.31  3067.6 3060.33 3060.13 3060.08 3059.98 3059.95 3059.87 3060.05
 3060.11 3060.13  3060.1  3059.5 3059.21 3058.68 3058.64 3058.63 3057.46 3056.55
 3056.16 3055.98 3055.46 3055.28 3055.26 3054.22    3054    3050    3050    3050
    3050    3054 3054.04 3054.06  3054.4 3055.44 3056.37 3056.94 3057.55 3058.51
 3059.21 3059.42 3059.62 3060.28 3060.91 3061.86  3061.8 3061.33 3062.13 3069.73
 3071.57 3078.64 3079.68
 3019.51 3019.51 3019.51 3019.51 3019.51 3019.51 3019.51 3019.51 3019.51 3019.51
 3019.51 3019.51 3019.51 3019.51 3019.51 3019.51 3019.51 3019.51 3019.51 3019.51
 3019.51 3019.51 3019.51 3019.51 3019.51 3019.51 3019.51 3019.51    3048    3048
 3019.51 3019.51 3019.51 3019.51 3019.51 3019.51 3019.51 3019.51 3019.51 3019.51
 3019.51 3019.51 3019.51 3019.51 3019.51 3019.51 3019.51 3019.51 3019.51 3019.51
 3019.51 3019.51 3019.51
  4830.8  4834.8  4845.3  4862.6  4867.4  4867.9  4877.5    4879  4883.4  4890.5
    4893  4893.7  4897.4  4903.8  4906.7  4911.4  4911.7  4911.8  4921.6  4933.4
  4936.7  4938.9  4949.8    4952  4952.5  4955.8  4956.5    4990    4990    5010
    5010  5036.4  5036.6  5036.7  5039.2    5047  5051.1  5054.5  5057.7  5064.8
  5069.8  5073.5  5076.3  5079.1  5083.1  5089.8  5090.3  5095.1  5096.1  5107.4
  5109.6  5119.6  5145.1
 3072.51 3071.31  3067.6 3060.33 3060.13 3060.08 3059.98 3059.95 3059.87 3060.05
 3060.11 3060.13  3060.1  3059.5 3059.21 3058.68 3058.64 3058.63 3057.46 3056.55
 3056.16 3055.98 3055.46 3055.28 3055.26 3054.22    3054    3050    3050    3050
    3050    3054 3054.04 3054.06  3054.4 3055.44 3056.37 3056.94 3057.55 3058.51
 3059.21 3059.42 3059.62 3060.28 3060.91 3061.86  3061.8 3061.33 3062.13 3069.73
 3071.57 3078.64 3079.68
 3019.51 3019.51 3019.51 3019.51 3019.51 3019.51 3019.51 3019.51 3019.51 3019.51
 3019.51 3019.51 3019.51 3019.51 3019.51 3019.51 3019.51 3019.51 3019.51 3019.51
 3019.51 3019.51 3019.51 3019.51 3019.51 3019.51 3019.51 3019.51    3048    3048
 3019.51 3019.51 3019.51 3019.51 3019.51 3019.51 3019.51 3019.51 3019.51 3019.51
 3019.51 3019.51 3019.51 3019.51 3019.51 3019.51 3019.51 3019.51 3019.51 3019.51
 3019.51 3019.51 3019.51
BR Coef= 1 , 1 , 0 ,1.25, 0 ,,,0.8,0,2,0,
WSPro=,,,, 1 ,,,, 0 ,,,, 0 ,,,,-1 ,-1 ,-1 , 0 , 0 , 0 , 0 , 0
BC Design=,, 0 ,, 0 ,,,,,,
BC HTab HWMax=3078.43

Type RM Length L Ch R = 1 ,11468   ,472,472,472
BEGIN DESCRIPTION:
XS9.2
END DESCRIPTION:
XS GIS Cut Line= 6
       797205.07       653103.33       797140.25       653066.54
       797103.46       653030.63       797062.29       652971.94
       797044.77       652914.13       796990.46       652923.76
#Sta/Elev= 30
  4831.2 3071.89  4836.6  3069.6    4850 3066.27    4866 3060.36  4871.4 3059.47
  4886.8 3059.43  4900.6 3059.92  4923.2 3057.44  4937.5 3056.41  4959.6 3051.16
  4974.5 3045.71 4994.53 3040.39    4996 3039.03    5004 3039.03    5005 3040.63
    5015 3045.39  5019.3 3047.43  5028.8 3050.07  5035.8 3051.48    5054  3054.3
  5060.4  3055.7  5067.1 3056.73  5073.9 3058.69  5085.3 3060.21  5100.2 3063.23
  5116.7  3064.6    5125 3064.35  5130.2  3068.6  5132.6 3070.82  5144.4 3079.17
#Mann= 4 ,-1 , 0
  4831.2     .09       0    4996     .05       0    5005    .055       0
    5015     .07       0
#XS Ineff= 2 , 0
       0    4971    3053    5020       0    3053
Permanent Ineff=
       F       F
Bank Sta=4994.53,5005
Exp/Cntr=0.5,0.3

Type RM Length L Ch R = 1 ,10996   ,483,483,483
BEGIN DESCRIPTION:
XS10
END DESCRIPTION:
XS GIS Cut Line= 5
        797517.8       652916.38       797515.86       652836.76
       797478.96       652780.44       797448.86       652735.78
       797338.16       652717.33
#Sta/Elev= 30
  4831.7 3084.81  4833.7 3083.32  4843.6 3077.07  4850.9 3072.01  4865.2 3061.45
  4885.2  3048.5  4893.7 3042.61  4897.2  3040.6  4907.5 3036.92  4927.3 3037.05
  4938.8 3036.44  4945.2 3035.33  4948.3 3033.16  4966.5 3019.14    4978 3013.69
  4983.5 3011.96    4992 3009.28  4995.3 3007.11  5004.7 3007.11  5009.2 3009.34
  5018.1 3012.29  5030.6 3013.65    5038 3015.21  5052.2 3017.43  5070.2 3019.46
  5093.1 3023.37  5102.6 3025.77  5117.6 3028.86  5129.8 3032.45  5144.8 3036.22
#Mann= 5 ,-1 , 0
  4831.7     .09       0  4983.5    .055       0    4992     .05       0
  5009.2    .055       0  5018.1     .06       0
Bank Sta=4992,5009.2
Exp/Cntr=0.3,0.1

Type RM Length L Ch R = 1 ,10513   ,322,322,322
BEGIN DESCRIPTION:
XS11
END DESCRIPTION:
XS GIS Cut Line= 5
       797915.78       652723.47       797869.09       652558.12
       797814.62       652474.47       797769.88       652410.27
       797606.47       652320.78
#Sta/Elev= 30
  4693.4 3056.13    4712 3047.11  4730.1 3032.89  4734.3 3028.45  4741.6 3023.27
    4750 3022.76  4773.7 3020.47  4795.4 3019.82    4807 3019.03  4820.5 3016.06
  4840.2 3006.85  4843.8 3005.97  4847.8 3004.38  4891.3 2999.51    4901 2998.08
  4912.2 2995.76  4918.9 2994.89  4935.1 2993.86  4979.8 2992.33  4992.9 2990.74
  4995.3 2988.06  5004.7 2988.06  5017.1 2990.78  5032.7 2992.97  5060.6  2993.7
  5107.4 2996.46  5112.6 2996.38  5142.5 3002.05  5171.2 3006.83  5229.6 3013.77
#Mann= 6 ,-1 , 0
  4693.4     .09       0    4750     .06       0  4979.8    .055       0
  4992.9     .05       0  5017.1    .055       0  5032.7     .06       0
Bank Sta=4992.9,5017.1
Exp/Cntr=0.5,0.3

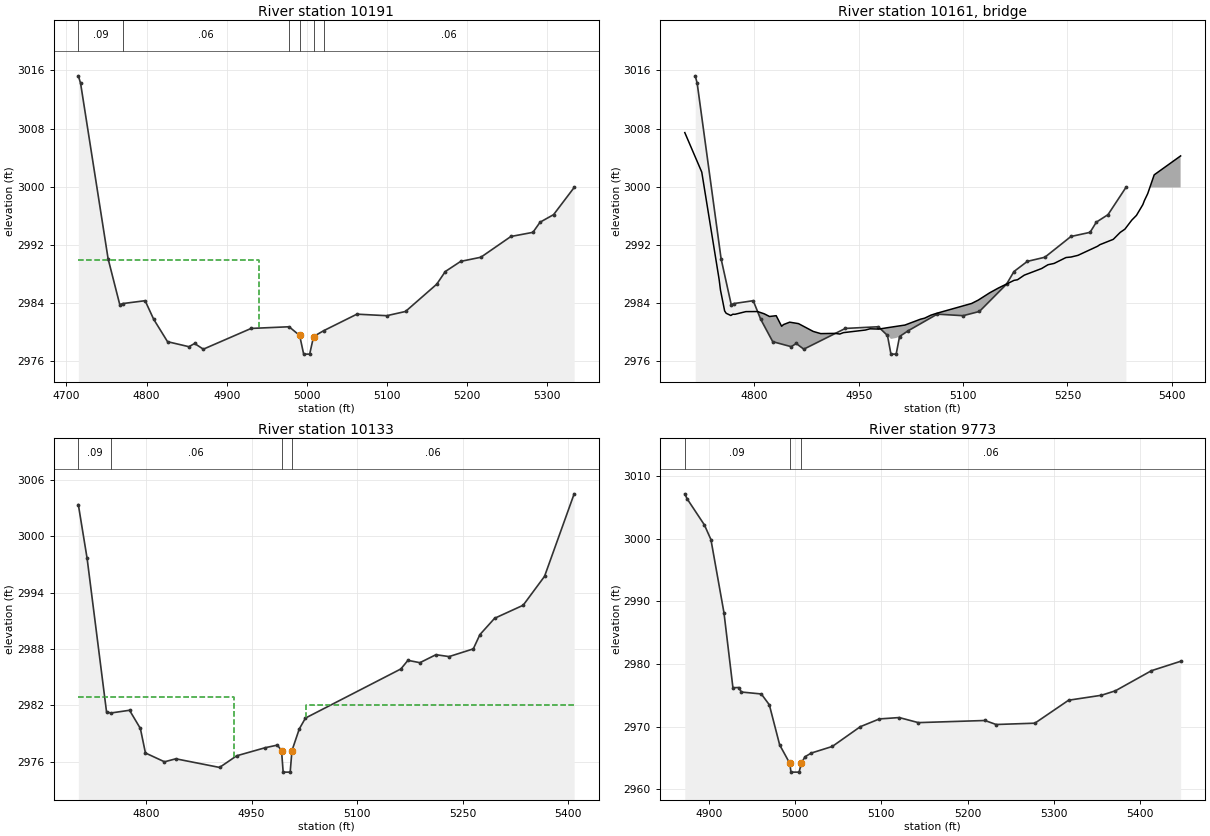
Type RM Length L Ch R = 1 ,10191   ,58,58,58
BEGIN DESCRIPTION:
XS12
END DESCRIPTION:
XS GIS Cut Line= 6
       798343.88       652368.37       798283.19       652323.46
       798137.54       652345.31       798046.51       652270.06
       797971.26       652155.97       797836.67       652122.42
#Sta/Elev= 30
  4714.8 3015.24  4717.6 3014.22    4752  2990.1  4766.6 2983.79    4770 2983.95
  4798.2 2984.35  4808.9  2981.8  4826.2 2978.72  4852.9 2978.03    4860 2978.47
  4870.9 2977.69  4930.6 2980.54    4978 2980.77  4991.2 2979.57  4996.2 2977.01
  5003.7 2977.01  5008.6 2979.43  5021.2 2980.23  5062.7  2982.5    5100 2982.29
  5123.4 2982.87  5162.4 2986.62  5173.1 2988.36  5192.3 2989.75  5217.5 2990.32
    5255 2993.17  5282.5 2993.74  5291.5 2995.14  5308.3 2996.17    5334  2999.9
#Mann= 6 ,-1 , 0
  4714.8     .09       0    4770     .06       0    4978    .055       0
  4991.2     .05       0  5008.6    .055       0  5021.2     .06       0
#XS Ineff= 3 ,-1
    4700    4940    2990    4940  4960.5    2980  5029.5    5200    2980
Permanent Ineff=
       F       F       F
Bank Sta=4991.2,5008.6
Exp/Cntr=0.5,0.3

Type RM Length L Ch R = 3 ,10161   ,,,
BEGIN DESCRIPTION:
XS13 TOR
Structure ID: Plott Creek 354
Approximate Survey Structure
END DESCRIPTION:
Bridge Culvert--1,0,-1,-1, 0
Deck Dist Width WeirC Skew NumUp NumDn MinLoCord MaxHiCord MaxSubmerge Is_Ogee
20,20,3,0, 60, 60, , , , 0, 1,1,,
  4699.8  4724.2  4749.2  4751.1  4757.1  4759.3  4765.9  4768.9  4771.9  4787.6
  4804.4    4814  4821.6  4831.2    4839  4841.7  4850.6  4863.3  4884.4  4895.2
  4916.1  4922.6  4927.8  4959.5  4966.1  4978.9  4990.5  4990.5  5009.1  5009.1
  5016.2  5038.7  5044.6  5053.6  5061.3  5112.2  5121.7  5138.1  5150.5  5173.1
  5178.2  5187.9  5212.9    5222  5230.8  5247.9  5255.2  5265.1  5293.3  5296.5
  5315.9  5325.8  5332.6  5342.4  5349.2  5358.4  5360.6  5365.4  5374.7  5412.7
 3007.44 3002.01 2987.24 2985.81 2982.94 2982.62 2982.32 2982.49 2982.48 2982.85
 2982.86 2982.55 2982.18 2982.29 2980.84 2981.07  2981.4  2981.2 2980.13 2979.83
 2979.86 2979.77 2979.96 2980.32 2980.49 2980.45 2980.63 2980.63  2980.9  2980.9
    2981 2981.81 2981.95 2982.36  2982.6 2983.97 2984.43 2985.43 2986.08 2987.14
 2987.23 2987.86 2988.77 2989.29 2989.47 2990.28 2990.35 2990.58 2991.83 2992.04
 2992.78 2993.73 2994.18 2995.41 2996.07 2997.55  2998.1 2999.06 3001.64 3004.24
    2956    2956    2956    2956    2956    2956    2956    2956    2956    2956
    2956    2956    2956    2956    2956    2956    2956    2956    2956    2956
    2956    2956    2956    2956    2956    2956    2956    2979 2979.32    2956
    2956    2956    2956    2956    2956    2956    2956    2956    2956    2956
    2956    2956    2956    2956    2956    2956    2956    2956    2956    2956
    2956    2956    2956    2956    2956    2956    2956    2956    2956    2956
  4699.8  4724.2  4749.2  4751.1  4757.1  4759.3  4765.9  4768.9  4771.9  4787.6
  4804.4    4814  4821.6  4831.2    4839  4841.7  4850.6  4863.3  4884.4  4895.2
  4916.1  4922.6  4927.8  4959.5  4966.1  4978.9  4990.5  4990.5  5009.1  5009.1
  5016.2  5038.7  5044.6  5053.6  5061.3  5112.2  5121.7  5138.1  5150.5  5173.1
  5178.2  5187.9  5212.9    5222  5230.8  5247.9  5255.2  5265.1  5293.3  5296.5
  5315.9  5325.8  5332.6  5342.4  5349.2  5358.4  5360.6  5365.4  5374.7  5412.7
 3007.44 3002.01 2987.24 2985.81 2982.94 2982.62 2982.32 2982.49 2982.48 2982.85
 2982.86 2982.55 2982.18 2982.29 2980.84 2981.07  2981.4  2981.2 2980.13 2979.83
 2979.86 2979.77 2979.96 2980.32 2980.49 2980.45 2980.63 2980.63  2980.9  2980.9
    2981 2981.81 2981.95 2982.36  2982.6 2983.97 2984.43 2985.43 2986.08 2987.14
 2987.23 2987.86 2988.77 2989.29 2989.47 2990.28 2990.35 2990.58 2991.83 2992.04
 2992.78 2993.73 2994.18 2995.41 2996.07 2997.55  2998.1 2999.06 3001.64 3004.24
    2956    2956    2956    2956    2956    2956    2956    2956    2956    2956
    2956    2956    2956    2956    2956    2956    2956    2956    2956    2956
    2956    2956    2956    2956    2956    2956    2956    2979 2979.32    2956
    2956    2956    2956    2956    2956    2956    2956    2956    2956    2956
    2956    2956    2956    2956    2956    2956    2956    2956    2956    2956
    2956    2956    2956    2956    2956    2956    2956    2956    2956    2956
Abutment Skew #Up #Dn= , 2 , 2
  4990.5  4991.5
    2979 2979.69
  4990.5  4991.9
    2979 2977.33
Abutment Skew #Up #Dn= , 2 , 2
  5008.5  5009.5
 2979.41    2979
    5008  5009.1
 2977.36 2979.34
BR Coef= 1 , 1 , 0 ,1.25, 0 ,,,0.8,0,2,0,
WSPro=,,,, 1 ,,,, 0 ,,,, 0 ,,,,-1 ,-1 ,-1 , 0 , 0 , 0 , 0 , 0
BC Design=,, 0 ,, 0 ,,,,,,
BC HTab HWMax=3015.24

Type RM Length L Ch R = 1 ,10133   ,360,360,360
BEGIN DESCRIPTION:
XS14
END DESCRIPTION:
XS GIS Cut Line= 6
       798386.36       652334.39       798329.32       652257.92
       798144.82       652291.91       798120.55       652268.84
       797994.32       652058.87       797852.31       652041.87
#Sta/Elev= 30
  4703.8 3003.39  4716.3 2997.65  4743.9 2981.31    4750 2981.19  4776.6 2981.48
    4792 2979.54  4799.2 2976.93  4826.3 2975.99  4842.4 2976.31  4904.6 2975.39
  4928.9 2976.63  4969.4 2977.49  4986.8 2977.77  4992.7 2977.18    4995 2974.89
    5005 2974.89  5007.5 2977.18  5017.9 2979.49  5026.7 2980.65  5162.3 2985.88
  5172.4  2986.8  5189.4 2986.55  5212.2  2987.4  5230.9  2987.2  5265.3 2988.02
  5274.7 2989.54  5295.6 2991.28  5336.2 2992.67  5366.6 2995.75  5408.7 3004.54
#Mann= 4 ,-1 , 0
  4703.8     .09       0    4750     .06       0  4992.7     .05       0
  5007.5     .06       0
#XS Ineff= 2 , 0
       0    4925  2982.9 5027.08       0    2982
Permanent Ineff=
       F       F
Bank Sta=4992.7,5007.5
Exp/Cntr=0.5,0.3

Type RM Length L Ch R = 1 ,9773    ,273,273,273
BEGIN DESCRIPTION:
XS14.5
END DESCRIPTION:
XS GIS Cut Line= 5
       798497.32        652312.2       798494.02       652236.39
       798470.95       652144.11       798327.58       651959.54
       798159.49       651933.17
#Sta/Elev= 30
  4872.2 3007.18  4874.9 3006.38  4894.9 3002.22  4902.5 2999.87  4917.6  2988.2
    4928  2976.2  4934.7 2976.23  4937.8 2975.51  4960.9  2975.2  4970.2 2973.47
  4982.2 2967.06  4993.9 2964.12  4995.3 2962.71  5004.7 2962.71 5007.44 2964.17
  5011.6 2965.17  5018.9 2965.76  5043.2 2966.81  5075.7 2969.97  5097.8 2971.21
  5120.8 2971.43    5143 2970.62  5220.2 2970.96  5233.2 2970.32  5278.1 2970.53
  5317.2  2974.2  5355.2 2974.99  5371.4  2975.7  5413.3 2978.92  5447.1 2980.42
#Mann= 3 ,-1 , 0
  4872.2     .09       0  4993.9     .05       0 5007.44     .06       0
Bank Sta=4993.9,5007.44
Exp/Cntr=0.5,0.3