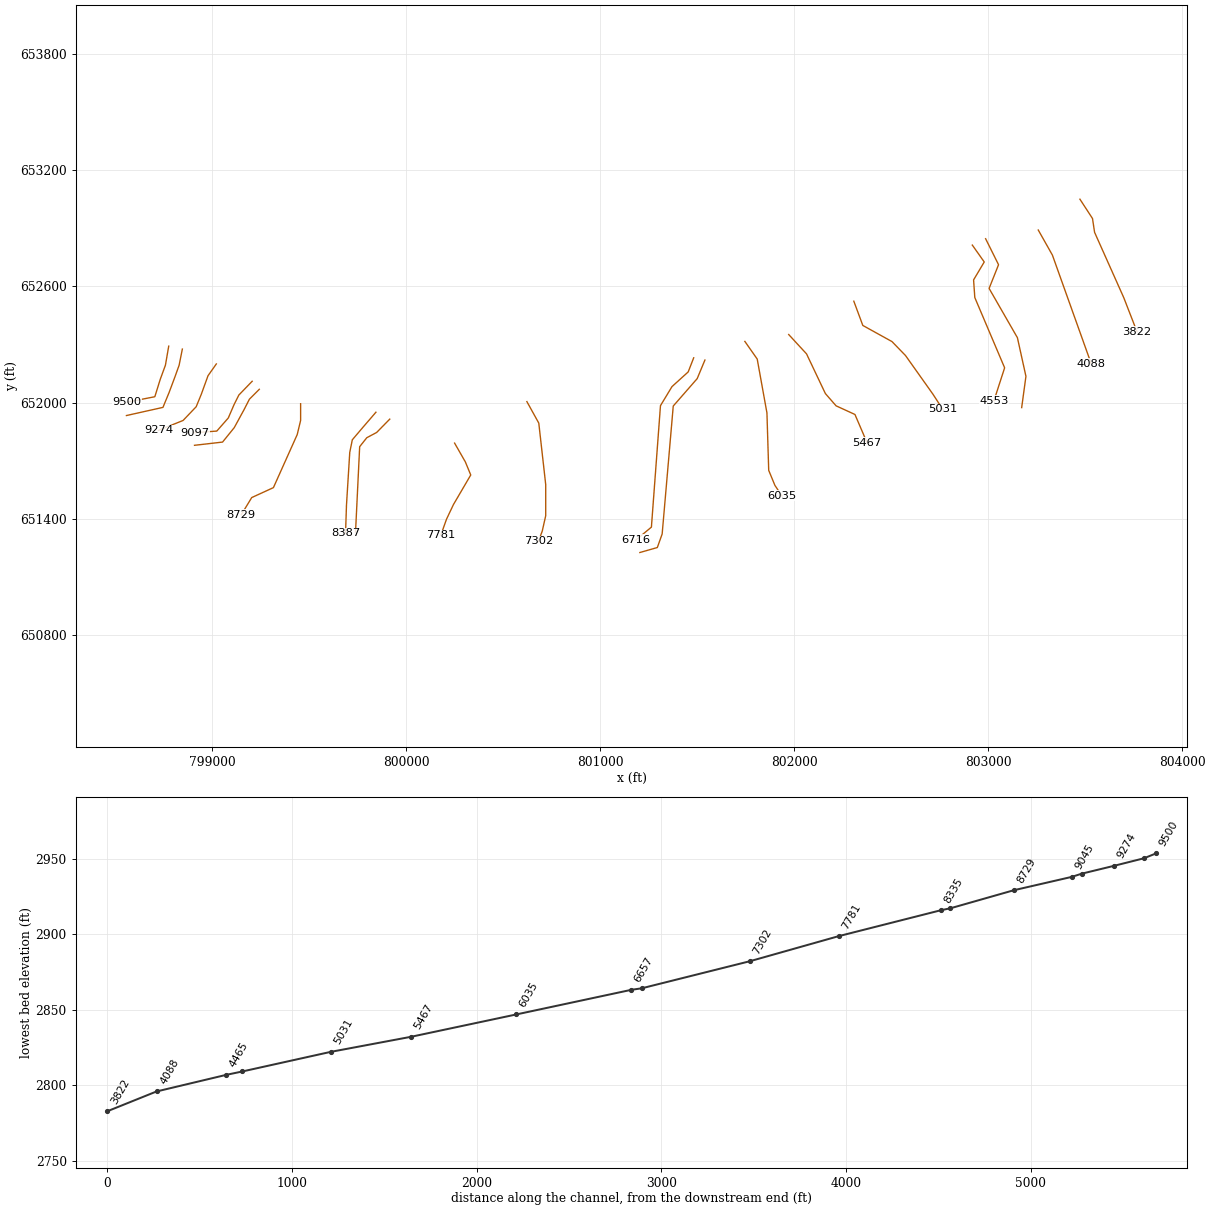
HEC-RAS study lds_plott_crk.prj: Plott Creek Limited Detail Study

--- lds_plott_crk.g01 (geometry) --- (continued)

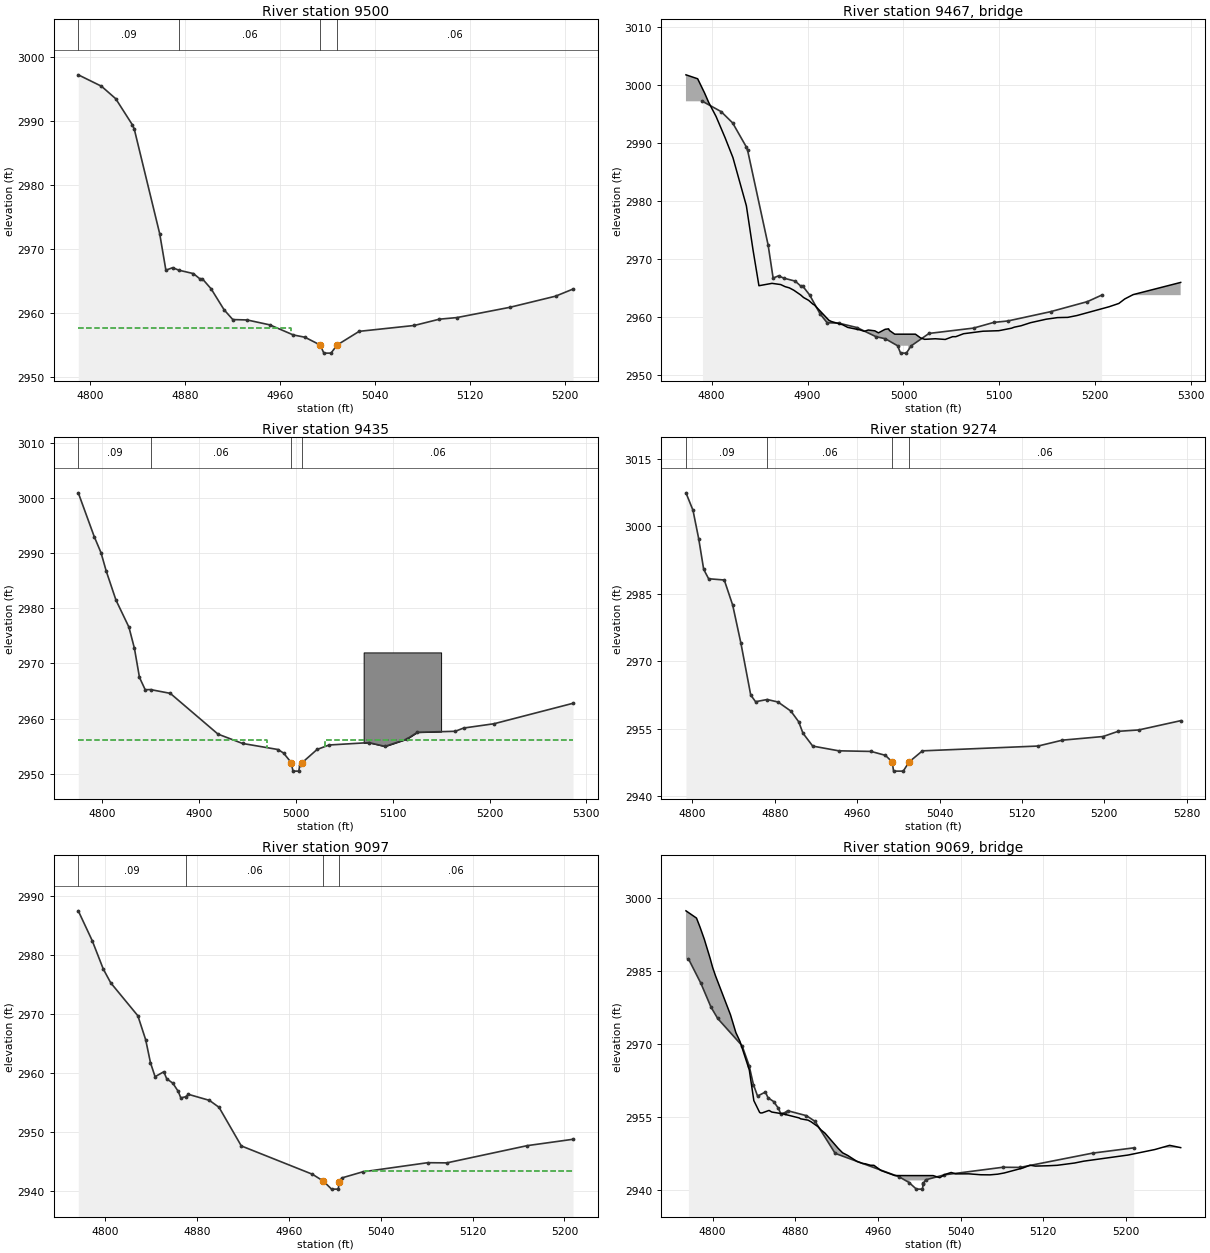
Type RM Length L Ch R = 1 ,9500    ,65,65,65
BEGIN DESCRIPTION:
XS15
END DESCRIPTION:
XS GIS Cut Line= 5
       798775.98       652291.91       798758.98       652193.59
       798732.28       652120.77       798704.37       652030.95
       798562.36       652003.03
#Sta/Elev= 30
  4790.4 2997.18  4809.9  2995.4  4821.9 2993.45    4836 2989.35  4837.5 2988.71
  4858.9 2972.37  4864.1 2966.68  4869.8 2967.07    4875 2966.68  4887.2 2966.15
  4892.7 2965.33  4894.9 2965.31  4902.2 2963.76  4913.1 2960.49  4920.4 2958.97
  4932.4 2958.91  4951.6 2958.14  4971.3 2956.57  4981.1 2956.21  4993.9    2955
    4997 2953.73    5003 2953.73  5008.2    2955  5026.7 2957.13  5073.1 2958.05
  5094.2 2959.03  5108.9 2959.28  5153.4 2960.88  5191.9 2962.62  5206.6 2963.73
#Mann= 4 ,-1 , 0
  4790.4     .09       0    4875     .06       0  4993.9     .05       0
  5008.2     .06       0
#XS Ineff= 2 , 0
       0    4969  2957.6    5031       0 2956.19
Permanent Ineff=
       F       F
Bank Sta=4993.9,5008.2
Exp/Cntr=0.5,0.3

Type RM Length L Ch R = 3 ,9467    ,,,
BEGIN DESCRIPTION:
XS16 TOR
Structure ID: XS16
Approximate Survey Structure
END DESCRIPTION:
Bridge Culvert--1,0,-1,-1, 0
Deck Dist Width WeirC Skew NumUp NumDn MinLoCord MaxHiCord MaxSubmerge Is_Ogee
26,14,3,0, 60, 60, , , , 0, 1,1,,
  4773.2  4785.4  4792.6  4796.9  4804.6  4813.9  4822.2  4836.2  4843.2  4849.3
  4862.9    4872  4876.6    4881  4885.6  4892.8  4895.8  4901.1  4905.7  4907.2
  4922.4    4925  4936.5  4941.9  4954.8  4959.2  4963.3  4970.1  4973.9  4980.9
  4984.5  4985.4  4990.9    4995    4995    5005    5005  5012.5  5017.9  5022.1
  5033.2  5043.6  5051.3  5054.6  5062.7  5082.9  5099.4  5112.7  5115.6  5122.6
  5132.5    5149  5160.7  5171.4    5181  5214.4  5224.6  5230.8  5239.6  5289.1
 3001.75 3001.07 2998.62 2996.99 2994.56 2990.94 2987.46 2979.15 2971.47 2965.36
 2965.77 2965.56  2965.2 2964.99 2964.59 2963.77 2963.33 2962.84 2962.17 2962.03
 2959.38 2959.18 2958.63 2958.17 2957.73 2957.49 2957.72 2957.58 2957.23 2957.84
 2957.92 2957.64    2957    2957    2957    2957    2957    2957 2956.35 2956.11
 2956.21 2956.09 2956.57 2956.57 2957.08 2957.51  2957.6 2958.03 2958.21 2958.45
 2958.98 2959.59 2959.86  2959.9 2960.22 2961.73  2962.3 2963.08 2963.83 2965.93
    2932    2932    2932    2932    2932    2932    2932    2932    2932    2932
    2932    2932    2932    2932    2932    2932    2932    2932    2932    2932
    2932    2932    2932    2932    2932    2932    2932    2932    2932    2932
    2932    2932    2932    2932    2955    2955    2932    2932    2932    2932
    2932    2932    2932    2932    2932    2932    2932    2932    2932    2932
    2932    2932    2932    2932    2932    2932    2932    2932    2932    2932
  4773.2  4785.4  4792.6  4796.9  4804.6  4813.9  4822.2  4836.2  4843.2  4849.3
  4862.9    4872  4876.6    4881  4885.6  4892.8  4895.8  4901.1  4905.7  4907.2
  4922.4    4925  4936.5  4941.9  4954.8  4959.2  4963.3  4970.1  4973.9  4980.9
  4984.5  4985.4  4990.9    4995    4995    5005    5005  5012.5  5017.9  5022.1
  5033.2  5043.6  5051.3  5054.6  5062.7  5082.9  5099.4  5112.7  5115.6  5122.6
  5132.5    5149  5160.7  5171.4    5181  5214.4  5224.6  5230.8  5239.6  5289.1
 3001.75 3001.07 2998.62 2996.99 2994.56 2990.94 2987.46 2979.15 2971.47 2965.36
 2965.77 2965.56  2965.2 2964.99 2964.59 2963.77 2963.33 2962.84 2962.17 2962.03
 2959.38 2959.18 2958.63 2958.17 2957.73 2957.49 2957.72 2957.58 2957.23 2957.84
 2957.92 2957.64    2957    2957    2957    2957    2957    2957 2956.35 2956.11
 2956.21 2956.09 2956.57 2956.57 2957.08 2957.51  2957.6 2958.03 2958.21 2958.45
 2958.98 2959.59 2959.86  2959.9 2960.22 2961.73  2962.3 2963.08 2963.83 2965.93
    2932    2932    2932    2932    2932    2932    2932    2932    2932    2932
    2932    2932    2932    2932    2932    2932    2932    2932    2932    2932
    2932    2932    2932    2932    2932    2932    2932    2932    2932    2932
    2932    2932    2932    2932    2955    2955    2932    2932    2932    2932
    2932    2932    2932    2932    2932    2932    2932    2932    2932    2932
    2932    2932    2932    2932    2932    2932    2932    2932    2932    2932
BR Coef= 1 , 1 , 0 ,1.25, 0 ,,,0.8,0,2,0,
WSPro=,,,, 1 ,,,, 0 ,,,, 0 ,,,,-1 ,-1 ,-1 , 0 , 0 , 0 , 0 , 0
BC Design=,, 0 ,, 0 ,,,,,,
BC HTab HWMax=2997.18

Type RM Length L Ch R = 1 ,9435    ,161,161,161
BEGIN DESCRIPTION:
XS17
END DESCRIPTION:
XS GIS Cut Line= 6
       798846.25       652276.81       798829.58       652193.45
       798808.75       652135.33        798778.4       652054.01
       798746.22       651975.95       798557.99       651933.88
#Sta/Elev= 30
  4775.3 3000.89  4791.8 2992.95  4798.8 2990.04  4804.1 2986.76  4814.2 2981.48
  4827.6 2976.58  4833.3 2972.73  4838.5 2967.47  4844.4 2965.25    4850 2965.27
  4870.3 2964.59  4919.6 2957.21  4944.9 2955.52  4981.6 2954.42  4987.3 2953.78
  4995.2 2952.06    4997 2950.51    5003 2950.51  5004.1 2951.63  5006.6 2952.06
  5021.9 2954.43  5034.3 2955.24  5075.4 2955.67    5092 2954.99  5114.5 2956.31
  5125.4 2957.54  5164.5 2957.72  5173.3 2958.31  5204.7 2959.09  5286.2 2962.79
#Mann= 4 ,-1 , 0
  4775.3     .09       0    4850     .06       0  4995.2     .05       0
  5006.6     .06       0
#XS Ineff= 2 , 0
       0    4970 2956.19    5030       0 2956.19
Permanent Ineff=
       F       F
#Block Obstruct= 1 ,-1
    5070    5150    2972
Bank Sta=4995.2,5006.6
Exp/Cntr=0.5,0.3

Type RM Length L Ch R = 1 ,9274    ,177,177,177
BEGIN DESCRIPTION:
XS17.5
END DESCRIPTION:
XS GIS Cut Line= 6
       799021.36       652200.14       798978.51       652139.17
       798943.91       652043.59       798917.54       651979.32
       798849.97       651908.46       798723.08       651857.37
#Sta/Elev= 30
  4793.7 3007.44  4800.5 3003.58  4806.1 2997.21  4810.9 2990.43  4815.7 2988.33
  4830.9 2988.05  4839.1 2982.45  4847.1 2973.95  4856.6 2962.46  4861.3 2960.98
  4872.6 2961.47  4883.1 2960.91  4895.6 2958.89  4903.2 2956.51  4907.3 2953.98
  4916.8 2951.11    4942 2950.06  4973.5 2949.92  4987.4 2949.05    4994 2947.57
  4995.3 2945.54  5004.7 2945.54 5010.39 2947.58  5023.3 2950.05  5135.6 2951.12
  5159.3 2952.43  5198.8 2953.24  5213.3 2954.39  5233.4  2954.7  5274.1 2956.76
#Mann= 4 ,-1 , 0
  4793.7     .09       0  4872.6     .06       0    4994     .05       0
 5010.39     .06       0
Bank Sta=4994,5010.39
Exp/Cntr=0.5,0.3

Type RM Length L Ch R = 1 ,9097    ,52,52,52
BEGIN DESCRIPTION:
XS18
END DESCRIPTION:
XS GIS Cut Line= 6
       799206.21       652110.73       799137.53       652039.68
       799112.67       651989.95       799083.07       651921.27
       799023.86       651853.78       798912.56       651845.49
#Sta/Elev= 30
  4776.6 2987.55  4788.7  2982.5  4798.4 2977.65  4804.9 2975.31  4828.5 2969.72
  4835.3 2965.65  4839.5 2961.73  4843.5 2959.37  4851.1 2960.21  4853.6 2959.03
    4859 2958.26  4863.7 2956.86  4865.9 2955.77    4870 2955.96  4872.6 2956.37
  4890.8 2955.35  4899.2 2954.17  4918.6 2947.61  4980.5  2942.8  4990.1 2941.63
  4997.2 2940.27    5003 2940.27  5003.9 2941.34    5004 2941.46  5006.1 2942.17
  5024.2  2943.2  5080.9 2944.76  5097.6 2944.73  5167.7 2947.66  5207.5 2948.74
#Mann= 4 ,-1 , 0
  4776.6     .09       0    4870     .06       0  4990.1     .05       0
  5003.9     .06       0
#XS Ineff= 2 , 0
       0    4974 2943.24    5026       0 2943.36
Permanent Ineff=
       F       F
Bank Sta=4990.1,5004
Exp/Cntr=0.5,0.3

Type RM Length L Ch R = 3 ,9069    ,,,
BEGIN DESCRIPTION:
XS19 TOR
Structure ID: XS19
Approximate Survey Structure
END DESCRIPTION:
Bridge Culvert--1,0,-1,-1, 0
Deck Dist Width WeirC Skew NumUp NumDn MinLoCord MaxHiCord MaxSubmerge Is_Ogee
21,14,3,0, 60, 60, , , , 0, 1,1,,
  4774.2  4784.4  4787.8    4792  4797.6    4800  4802.8  4817.3  4822.5  4826.5
  4835.5  4839.9  4845.5  4846.6  4848.1  4854.6  4857.2  4868.1  4883.7  4885.3
  4892.4  4895.5    4902  4904.8  4908.8  4921.6  4925.8  4930.8  4939.7  4945.1
  4947.7  4952.8  4956.1    4963  4976.3  4990.5  4990.5  5009.5  5009.5  5013.4
  5019.9  5024.7  5030.9  5035.3  5047.9  5059.6  5068.4  5075.9  5082.3  5100.4
  5107.2  5112.3  5124.8  5133.4  5150.3  5159.2  5202.1    5228  5242.3    5253
 2997.41 2995.92 2994.07 2991.55 2987.65  2985.8 2984.07 2976.06 2972.41 2970.59
 2964.73 2958.44 2956.02  2955.9 2955.93 2956.43  2956.1 2955.72 2954.89  2954.7
 2954.43 2954.07 2953.09 2952.45 2951.75 2948.62 2947.73 2947.18 2945.96 2945.54
 2945.48 2945.17 2945.16 2944.09 2943.06 2943.05 2943.05 2943.05 2943.05 2943.05
 2942.61 2943.27 2943.69  2943.4 2943.41 2943.22  2943.2 2943.34 2943.59 2944.62
 2945.18    2945 2945.07 2945.16 2945.63 2946.01 2947.27  2948.4 2949.26 2948.79
    2918    2918    2918    2918    2918    2918    2918    2918    2918    2918
    2918    2918    2918    2918    2918    2918    2918    2918    2918    2918
    2918    2918    2918    2918    2918    2918    2918    2918    2918    2918
    2918    2918    2918    2918    2918    2918 2942.05 2942.05    2918    2918
    2918    2918    2918    2918    2918    2918    2918    2918    2918    2918
    2918    2918    2918    2918    2918    2918    2918    2918    2918    2918
  4774.2  4784.4  4787.8    4792  4797.6    4800  4802.8  4817.3  4822.5  4826.5
  4835.5  4839.9  4845.5  4846.6  4848.1  4854.6  4857.2  4868.1  4883.7  4885.3
  4892.4  4895.5    4902  4904.8  4908.8  4921.6  4925.8  4930.8  4939.7  4945.1
  4947.7  4952.8  4956.1    4963  4976.3  4990.5  4990.5  5009.5  5009.5  5013.4
  5019.9  5024.7  5030.9  5035.3  5047.9  5059.6  5068.4  5075.9  5082.3  5100.4
  5107.2  5112.3  5124.8  5133.4  5150.3  5159.2  5202.1    5228  5242.3    5253
 2997.41 2995.92 2994.07 2991.55 2987.65  2985.8 2984.07 2976.06 2972.41 2970.59
 2964.73 2958.44 2956.02  2955.9 2955.93 2956.43  2956.1 2955.72 2954.89  2954.7
 2954.43 2954.07 2953.09 2952.45 2951.75 2948.62 2947.73 2947.18 2945.96 2945.54
 2945.48 2945.17 2945.16 2944.09 2943.06 2943.05 2943.05 2943.05 2943.05 2943.05
 2942.61 2943.27 2943.69  2943.4 2943.41 2943.22  2943.2 2943.34 2943.59 2944.62
 2945.18    2945 2945.07 2945.16 2945.63 2946.01 2947.27  2948.4 2949.26 2948.79
    2918    2918    2918    2918    2918    2918    2918    2918    2918    2918
    2918    2918    2918    2918    2918    2918    2918    2918    2918    2918
    2918    2918    2918    2918    2918    2918    2918    2918    2918    2918
    2918    2918    2918    2918    2918    2918 2942.05 2942.05    2918    2918
    2918    2918    2918    2918    2918    2918    2918    2918    2918    2918
    2918    2918    2918    2918    2918    2918    2918    2918    2918    2918
BR Coef= 1 , 1 , 0 ,1.25, 0 ,,,0.8,0,2,0,
WSPro=,,,, 1 ,,,, 0 ,,,, 0 ,,,,-1 ,-1 ,-1 , 0 , 0 , 0 , 0 , 0
BC Design=,, 0 ,, 0 ,,,,,,
BC HTab HWMax=2987.55

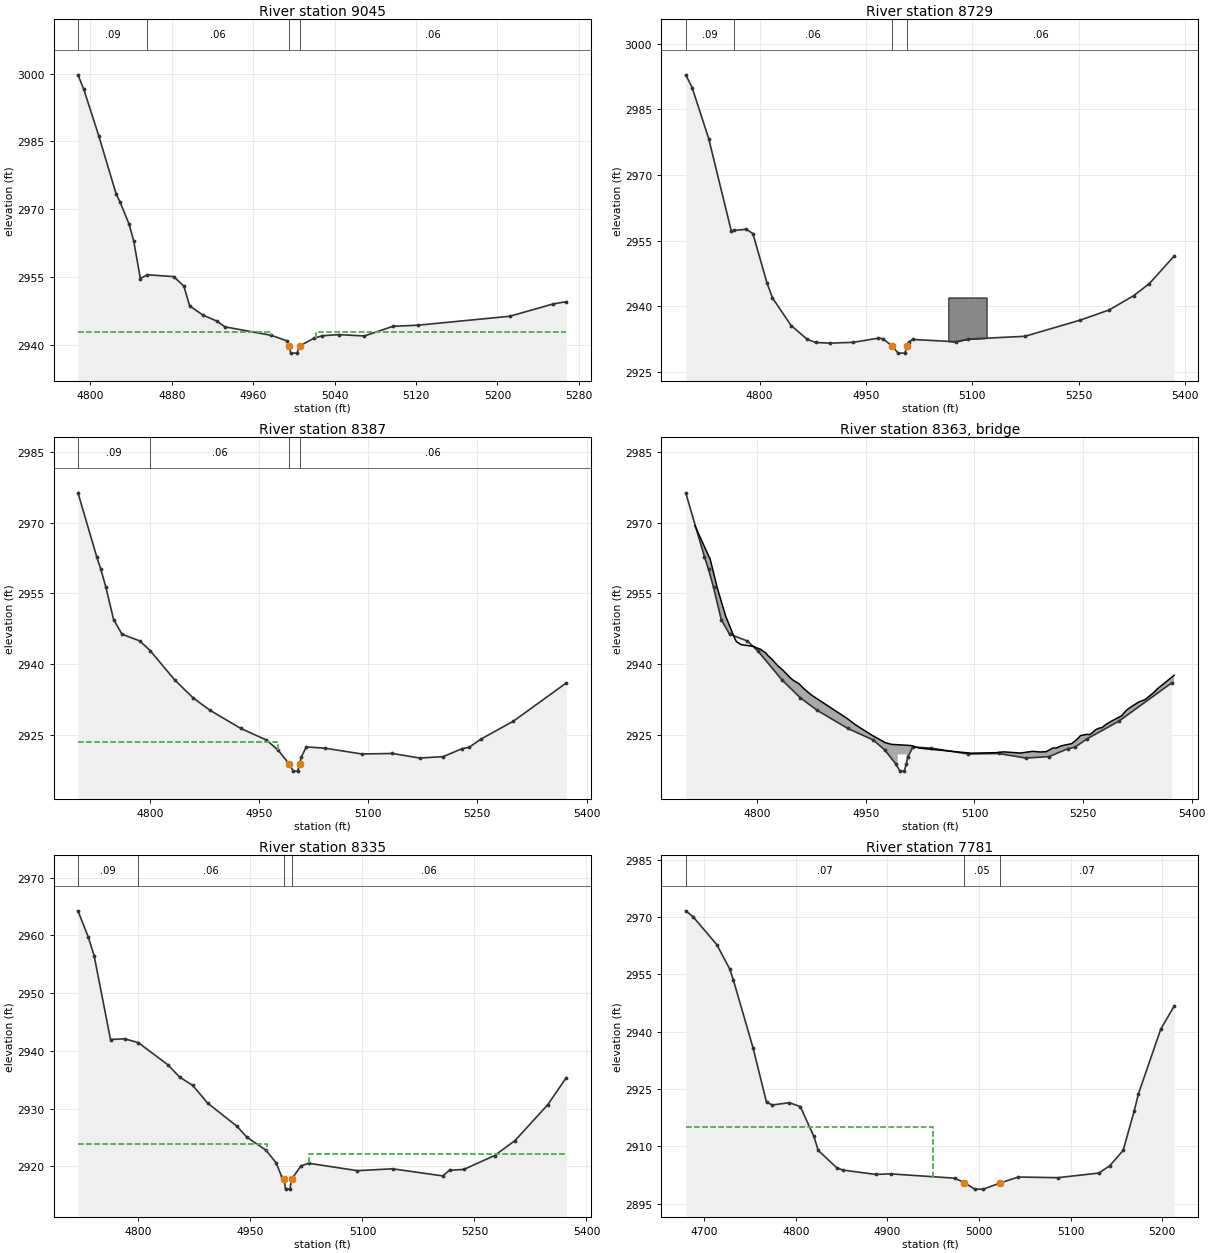
Type RM Length L Ch R = 1 ,9045    ,316,316,316
BEGIN DESCRIPTION:
XS20
END DESCRIPTION:
XS GIS Cut Line= 6
       799242.92       652069.28         799192.       652018.37
       799164.77       651965.08       799113.85       651871.54
       799053.46       651796.94       798909.01       651780.37
#Sta/Elev= 30
  4787.9 2999.71  4793.6 2996.52  4808.3 2986.26  4825.5 2973.32  4829.2 2971.62
    4838 2966.79  4842.6 2963.09  4849.2 2954.69  4856.2 2955.52    4882 2955.11
    4892 2953.01  4897.6 2948.64  4910.9 2946.58  4924.4 2945.28  4932.3 2944.01
    4978 2942.13  4992.9 2940.94  4995.3 2939.85    4997  2938.2    5003  2938.2
  5005.9 2939.82  5019.6 2941.46  5028.1 2942.05  5044.5 2942.29  5069.3 2941.99
  5097.3 2944.12  5122.3 2944.38  5212.2 2946.35  5254.8 2949.07  5267.7 2949.57
#Mann= 4 ,-1 , 0
  4787.9     .09       0  4856.2     .06       0  4995.3     .05       0
  5005.9     .06       0
#XS Ineff= 2 , 0
       0    4978 2942.88    5022       0  2942.9
Permanent Ineff=
       F       F
Bank Sta=4995.3,5005.9
Exp/Cntr=0.5,0.3

Type RM Length L Ch R = 1 ,8729    ,342,342,342
BEGIN DESCRIPTION:
XS21
END DESCRIPTION:
XS GIS Cut Line= 6
       799455.94       651994.84       799455.94       651908.53
       799438.41       651835.71       799315.69       651561.96
       799203.76       651510.71       799149.82       651421.71
#Sta/Elev= 30
  4695.8 2992.85  4704.8 2989.95  4728.2 2978.26  4759.9 2957.26  4763.4  2957.3
  4781.3 2957.56  4790.5 2956.58  4810.2 2945.39  4818.1  2941.9  4844.5 2935.56
  4867.1 2932.43  4879.1 2931.71  4899.3 2931.56  4932.1 2931.75  4967.4  2932.7
  4973.7 2932.58  4987.3 2930.83  4995.3 2929.28  5004.7 2929.28  5007.8 2930.88
  5010.3 2931.83  5015.8  2932.4  5076.3 2931.88  5094.2 2932.49  5174.1 2933.13
    5252 2936.82    5293 2939.16  5327.6 2942.43  5349.5 2945.17  5384.3 2951.43
#Mann= 4 ,-1 , 0
  4695.8     .09       0  4763.4     .06       0  4987.3     .05       0
  5007.8     .06       0
#Block Obstruct= 1 ,-1
    5066    5120    2942
Bank Sta=4987.3,5007.8
Exp/Cntr=0.5,0.3

Type RM Length L Ch R = 1 ,8387    ,52,52,52
BEGIN DESCRIPTION:
XS22
END DESCRIPTION:
XS GIS Cut Line= 6
        799844.2       651951.03       799776.73       651872.71
       799722.51       651808.85       799709.25       651743.78
       799692.38       651471.47       799687.56       651326.87
#Sta/Elev= 30
  4701.1  2976.3    4727 2962.71  4732.6 2960.08  4739.5 2956.28  4750.1 2949.46
  4761.6 2946.36  4786.1 2944.93  4800.4 2942.87  4834.2 2936.65  4859.4 2932.87
  4882.5 2930.25  4924.9  2926.4    4960 2923.96  4976.2 2921.81    4991 2918.93
  4997.2 2917.36    5003 2917.38  5005.9 2918.94  5007.8 2920.25  5014.9 2922.49
  5040.5 2922.22  5091.3 2920.99  5133.2  2921.1  5170.8 2920.13    5203 2920.43
  5228.8  2922.1  5238.5  2922.4  5255.6  2924.2  5299.6 2927.95  5372.2 2936.03
#Mann= 4 ,-1 , 0
  4701.1     .09       0  4800.4     .06       0    4991     .05       0
  5005.9     .06       0
#XS Ineff= 2 , 0
       0    4976 2923.45    5024       0 2922.23
Permanent Ineff=
       F       F
Bank Sta=4991,5005.9
Exp/Cntr=0.5,0.3

Type RM Length L Ch R = 3 ,8363    ,,,
BEGIN DESCRIPTION:
XS23 TOR
Structure ID: XS23
Approximate Survey Structure
END DESCRIPTION:
Bridge Culvert--1,0,-1,-1, 0
Deck Dist Width WeirC Skew NumUp NumDn MinLoCord MaxHiCord MaxSubmerge Is_Ogee
18,12,3,0, 60, 60, , , , 0, 1,1,,
  4713.7  4732.9  4734.7  4744.7  4756.3  4768.5  4771.2  4777.6  4795.8  4797.8
  4803.9  4812.1  4814.4  4819.8  4828.3  4835.1    4845  4849.8  4857.6  4863.9
  4874.9  4924.5  4935.4  4958.2  4976.6  4985.8    4994    4994    5006    5006
  5012.2  5024.2  5095.2  5128.9  5140.7  5162.9  5180.5  5190.7    5199  5208.1
  5213.8  5219.7  5234.1  5240.9  5246.5  5255.3  5259.4  5267.6  5272.5    5276
  5281.2  5288.7  5303.3  5309.1  5312.7  5326.5  5335.8  5347.1  5352.7  5375.7
 2969.36 2962.87 2962.36 2956.14 2950.18 2945.57 2944.77 2944.15 2943.75 2943.52
 2943.21 2942.33 2941.86 2941.12 2939.67 2938.77 2937.21 2936.58 2935.87 2934.87
 2933.46 2928.46 2927.19 2924.98 2923.39 2923.02 2922.95 2922.95 2922.84 2922.84
 2922.78 2922.22 2921.16 2921.26 2921.44 2921.19 2921.55 2921.41 2921.48 2922.23
 2922.29 2922.71 2923.18 2923.98 2924.88 2925.16 2925.08 2926.14 2926.48 2926.55
  2927.2  2927.9 2929.08 2930.14 2930.58 2931.97 2932.52 2933.93  2934.8 2937.65
    2897    2897    2897    2897    2897    2897    2897    2897    2897    2897
    2897    2897    2897    2897    2897    2897    2897    2897    2897    2897
    2897    2897    2897    2897    2897    2897    2897  2920.9  2920.9    2897
    2897    2897    2897    2897    2897    2897    2897    2897    2897    2897
    2897    2897    2897    2897    2897    2897    2897    2897    2897    2897
    2897    2897    2897    2897    2897    2897    2897    2897    2897    2897
  4713.7  4732.9  4734.7  4744.7  4756.3  4768.5  4771.2  4777.6  4795.8  4797.8
  4803.9  4812.1  4814.4  4819.8  4828.3  4835.1    4845  4849.8  4857.6  4863.9
  4874.9  4924.5  4935.4  4958.2  4976.6  4985.8    4994    4994    5006    5006
  5012.2  5024.2  5095.2  5128.9  5140.7  5162.9  5180.5  5190.7    5199  5208.1
  5213.8  5219.7  5234.1  5240.9  5246.5  5255.3  5259.4  5267.6  5272.5    5276
  5281.2  5288.7  5303.3  5309.1  5312.7  5326.5  5335.8  5347.1  5352.7  5375.7
 2969.36 2962.87 2962.36 2956.14 2950.18 2945.57 2944.77 2944.15 2943.75 2943.52
 2943.21 2942.33 2941.86 2941.12 2939.67 2938.77 2937.21 2936.58 2935.87 2934.87
 2933.46 2928.46 2927.19 2924.98 2923.39 2923.02 2922.95 2922.95 2922.84 2922.84
 2922.78 2922.22 2921.16 2921.26 2921.44 2921.19 2921.55 2921.41 2921.48 2922.23
 2922.29 2922.71 2923.18 2923.98 2924.88 2925.16 2925.08 2926.14 2926.48 2926.55
  2927.2  2927.9 2929.08 2930.14 2930.58 2931.97 2932.52 2933.93  2934.8 2937.65
    2897    2897    2897    2897    2897    2897    2897    2897    2897    2897
    2897    2897    2897    2897    2897    2897    2897    2897    2897    2897
    2897    2897    2897    2897    2897    2897    2897  2920.9  2920.9    2897
    2897    2897    2897    2897    2897    2897    2897    2897    2897    2897
    2897    2897    2897    2897    2897    2897    2897    2897    2897    2897
    2897    2897    2897    2897    2897    2897    2897    2897    2897    2897
BR Coef= 1 , 1 , 0 ,1.25, 0 ,,,0.8,0,2,0,
WSPro=,,,, 1 ,,,, 0 ,,,, 0 ,,,,-1 ,-1 ,-1 , 0 , 0 , 0 , 0 , 0
BC Design=,, 0 ,, 0 ,,,,,,
BC HTab HWMax=2976.3

Type RM Length L Ch R = 1 ,8335    ,554,554,554
BEGIN DESCRIPTION:
XS24
END DESCRIPTION:
XS GIS Cut Line= 6
       799915.48       651915.35       799847.99       651846.67
       799797.07       651819.44       799760.36       651773.26
        799742.6       651406.19       799739.05       651332.78
#Sta/Elev= 30
    4719 2964.26  4732.8 2959.72  4740.7 2956.47  4762.6 2941.97  4781.7 2942.09
    4800 2941.41  4839.4 2937.59  4855.2 2935.46  4872.8 2934.01  4892.7 2930.95
    4932 2926.93  4945.3 2925.04  4971.1 2922.76  4984.5 2920.58  4991.9 2918.18
    4995 2917.75    4997 2916.05    5003 2916.05    5005 2917.75  5017.7 2920.08
  5028.1 2920.53  5093.2 2919.25  5140.4 2919.57  5207.5 2918.34  5216.6 2919.32
  5235.6 2919.46  5276.9 2921.86  5304.3 2924.46  5348.1 2930.66    5373 2935.36
#Mann= 4 ,-1 , 0
    4719     .09       0    4800     .06       0    4995     .05       0
    5005     .06       0
#XS Ineff= 2 , 0
       0    4972 2923.83    5028       0 2922.18
Permanent Ineff=
       F       F
Bank Sta=4995,5005
Exp/Cntr=0.5,0.3

Type RM Length L Ch R = 1 ,7781    ,479,479,479
BEGIN DESCRIPTION:
XS25
END DESCRIPTION:
XS GIS Cut Line= 6
       800249.75       651791.73       800305.25       651694.61
         800333.       651627.22       800243.81        651474.6
       800208.13       651399.29        800178.4       651316.04
#Sta/Elev= 30
  4679.7 2971.59  4687.6 2970.07  4713.6 2962.77  4727.6 2956.45  4731.6  2953.6
  4753.3  2935.7  4767.9 2921.58  4774.3 2920.85  4792.9 2921.44  4804.8 2920.43
  4819.6 2912.65  4824.4 2908.96  4844.4 2904.49  4851.1 2903.83  4887.5 2902.69
  4903.4 2902.84  4973.4 2901.71  4983.7 2900.58  4995.3 2898.85  5004.7 2898.85
  5023.1 2900.46    5043 2902.02  5085.9 2901.84  5130.8 2903.05  5142.8 2904.97
  5157.4 2908.98  5169.5 2919.31    5174 2923.69  5198.5 2940.68    5213 2946.64
#Mann= 3 ,-1 , 0
  4679.7     .07       0  4983.7     .05       0  5023.1     .07       0
#XS Ineff= 2 , 0
       0    4950    2915               0
Permanent Ineff=
       F       F
#Block Obstruct= 1 ,-1
    4950    4910    2915
Bank Sta=4983.7,5023.1
Exp/Cntr=0.3,0.1

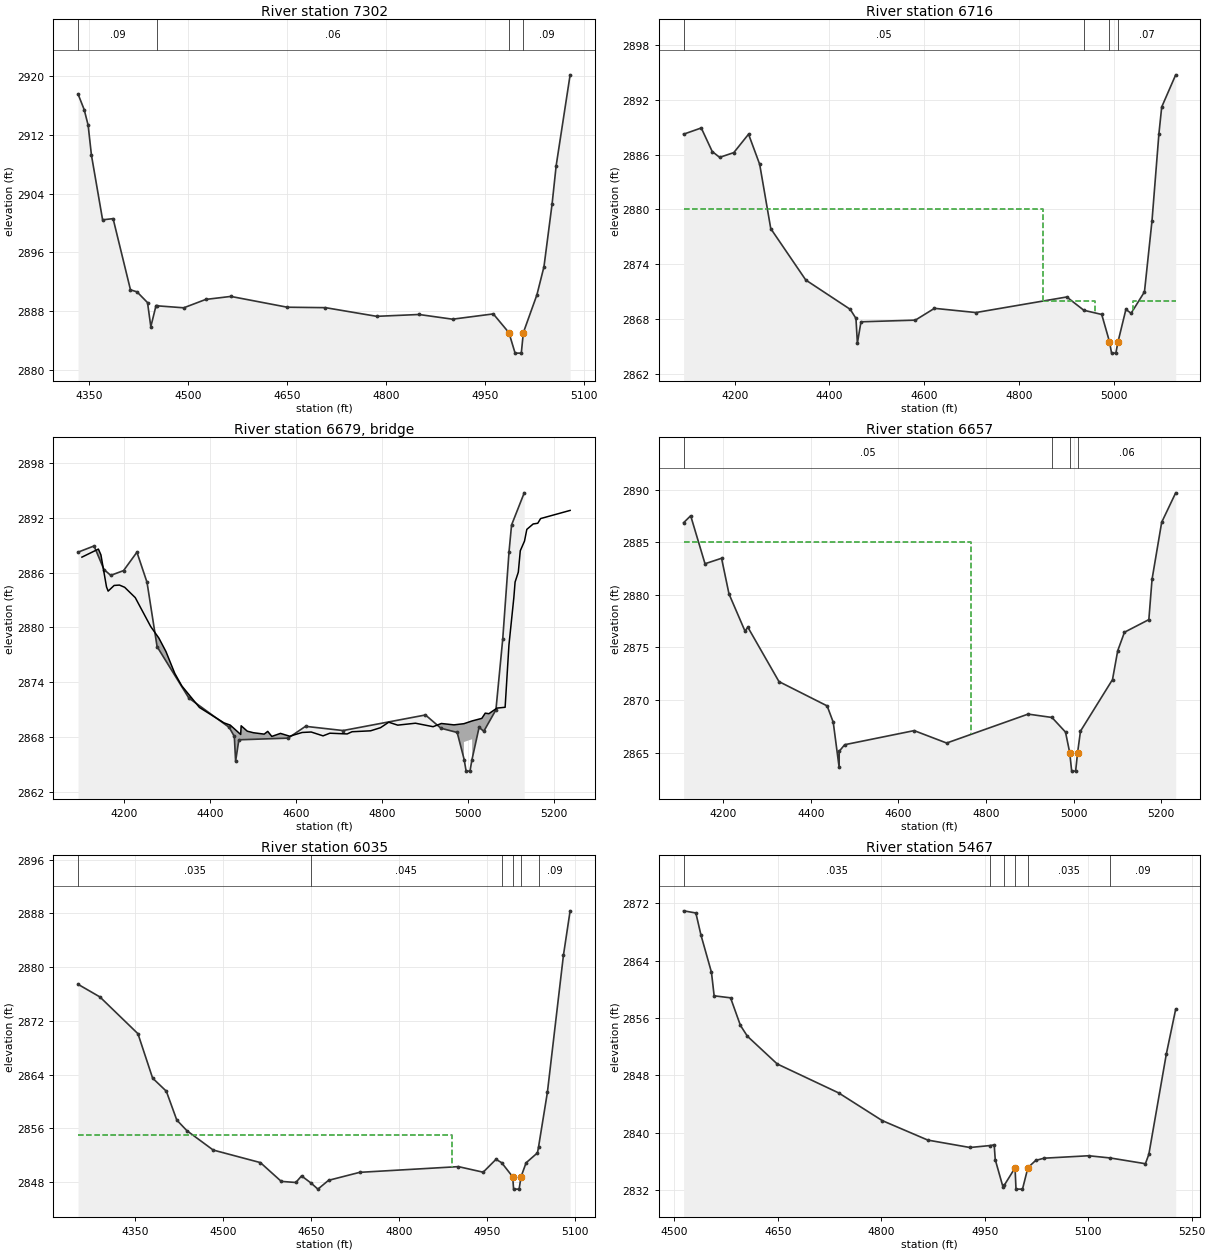
Type RM Length L Ch R = 1 ,7302    ,586,586,586
BEGIN DESCRIPTION:
XS26
END DESCRIPTION:
XS GIS Cut Line= 6
       800622.38       652005.79       800683.82        651894.8
        800719.5       651577.67        800719.5       651417.12
       800701.66       651337.84       800681.84       651284.33
#Sta/Elev= 30
  4333.7 2917.57    4343 2915.45    4349 2913.33    4354 2909.25  4370.9 2900.44
  4386.8  2900.6  4413.1 2890.91    4423 2890.63  4438.9 2889.17  4443.9 2885.89
  4451.8 2888.77  4453.7 2888.73  4493.7 2888.46    4527  2889.6    4565 2890.01
  4650.5 2888.54  4708.3 2888.48  4785.8  2887.3  4849.9 2887.55  4900.6 2886.91
  4962.3 2887.63    4986 2885.07  4995.3 2882.29  5004.7 2882.29  5007.8 2885.08
  5028.3 2890.22    5039 2894.05  5051.3  2902.6  5057.5 2907.83  5078.6 2920.18
#Mann= 4 ,-1 , 0
  4333.7     .09       0  4453.7     .06       0    4986     .05       0
  5007.8     .09       0
#XS Ineff= 2 , 0
       0  4791.5                       0
Permanent Ineff=
       T       F
Bank Sta=4986,5007.8
Exp/Cntr=0.5,0.3

Type RM Length L Ch R = 1 ,6716    ,59,59,59
BEGIN DESCRIPTION:
XS27
END DESCRIPTION:
XS GIS Cut Line= 6
       801482.41       652231.65       801454.14       652159.03
       801370.59        652083.2       801311.13       651984.95
        801264.4       651358.22       801184.07       651291.55
#Sta/Elev= 30
  4092.2 2888.22  4129.5  2888.9  4152.6 2886.33  4168.3 2885.69  4198.2 2886.21
  4229.3 2888.22  4252.8 2884.93  4276.2 2877.91  4350.1  2872.3  4443.9  2869.1
    4456 2868.11    4459  2865.4  4466.6 2867.74  4581.3 2867.92  4621.7 2869.21
  4709.1 2868.75  4900.9 2870.45  4936.9    2869  4974.7 2868.54    4991 2865.58
  4995.5 2864.32  5004.5 2864.32    5009 2865.54  5025.7 2869.09  5036.7 2868.67
  5064.9 2871.01  5080.8 2878.77  5095.4 2888.27  5101.3 2891.19  5130.8  2894.7
#Mann= 4 ,-1 , 0
  4092.2     .05       0  4936.9    .045       0    4991     .04       0
    5009     .07       0
#XS Ineff= 3 ,-1
  4850.7    4960    2870    5040  5130.8    2870  4092.2  4850.6    2880
Permanent Ineff=
       F       F       F
Bank Sta=4991,5009
Exp/Cntr=0.5,0.3

Type RM Length L Ch R = 3 ,6679    ,,,
BEGIN DESCRIPTION:
XS28 TOR
Structure ID: XS28
Approximate Survey Structure
END DESCRIPTION:
Bridge Culvert--1,0,-1,-1, 0
Deck Dist Width WeirC Skew NumUp NumDn MinLoCord MaxHiCord MaxSubmerge Is_Ogee
27.5,19,3,0, 60, 60, , , , 0, 1,1,,
  4101.3  4139.6  4145.5  4158.5  4162.3  4176.3  4188.6  4200.7  4225.4  4261.4
  4280.3  4296.8  4317.4  4333.8  4374.8  4431.9  4446.6  4470.8  4471.9  4486.2
  4500.7  4525.5  4533.8  4543.2  4563.4  4584.9  4613.9  4634.9  4662.5  4678.3
  4718.6    4730  4773.1  4796.2  4815.4  4836.3  4877.6  4918.6  4937.9  4967.3
  4990.5  4990.5  5009.5  5009.5  5032.1    5040  5048.5  5067.3  5086.3  5095.2
  5106.6  5109.5    5117  5121.6  5131.4  5136.8  5151.6  5162.3  5168.9  5237.6
 2887.68 2888.56 2887.93 2884.43 2883.97 2884.59 2884.63 2884.39 2883.26  2880.1
 2878.85 2877.38 2874.99 2873.62 2871.27 2869.59 2869.34 2868.32 2869.27 2868.68
 2868.51 2868.36 2868.66 2868.11 2868.44 2868.13 2868.54 2868.59 2868.17 2868.46
 2868.38 2868.62 2868.72 2869.06 2869.66 2869.34 2869.55 2869.17 2869.52 2869.37
  2869.5  2869.5  2869.8  2869.8 2870.08 2870.65 2870.59  2871.2 2871.29 2878.09
 2883.26 2884.96 2886.04 2888.38 2889.43 2890.71  2891.3 2891.38 2891.89 2892.78
    2844    2844    2844    2844    2844    2844    2844    2844    2844    2844
    2844    2844    2844    2844    2844    2844    2844    2844    2844    2844
    2844    2844    2844    2844    2844    2844    2844    2844    2844    2844
    2844    2844    2844    2844    2844    2844    2844    2844    2844    2844
    2844  2867.5  2867.8    2844    2844    2844    2844    2844    2844    2844
    2844    2844    2844    2844    2844    2844    2844    2844    2844    2844
  4101.3  4139.6  4145.5  4158.5  4162.3  4176.3  4188.6  4200.7  4225.4  4261.4
  4280.3  4296.8  4317.4  4333.8  4374.8  4431.9  4446.6  4470.8  4471.9  4486.2
  4500.7  4525.5  4533.8  4543.2  4563.4  4584.9  4613.9  4634.9  4662.5  4678.3
  4718.6    4730  4773.1  4796.2  4815.4  4836.3  4877.6  4918.6  4937.9  4967.3
  4990.5  4990.5  5009.5  5009.5  5032.1    5040  5048.5  5067.3  5086.3  5095.2
  5106.6  5109.5    5117  5121.6  5131.4  5136.8  5151.6  5162.3  5168.9  5237.6
 2887.68 2888.56 2887.93 2884.43 2883.97 2884.59 2884.63 2884.39 2883.26  2880.1
 2878.85 2877.38 2874.99 2873.62 2871.27 2869.59 2869.34 2868.32 2869.27 2868.68
 2868.51 2868.36 2868.66 2868.11 2868.44 2868.13 2868.54 2868.59 2868.17 2868.46
 2868.38 2868.62 2868.72 2869.06 2869.66 2869.34 2869.55 2869.17 2869.52 2869.37
  2869.5  2869.5  2869.8  2869.8 2870.08 2870.65 2870.59  2871.2 2871.29 2878.09
 2883.26 2884.96 2886.04 2888.38 2889.43 2890.71  2891.3 2891.38 2891.89 2892.78
    2844    2844    2844    2844    2844    2844    2844    2844    2844    2844
    2844    2844    2844    2844    2844    2844    2844    2844    2844    2844
    2844    2844    2844    2844    2844    2844    2844    2844    2844    2844
    2844    2844    2844    2844    2844    2844    2844    2844    2844    2844
    2844  2867.5  2867.8    2844    2844    2844    2844    2844    2844    2844
    2844    2844    2844    2844    2844    2844    2844    2844    2844    2844
BR Coef= 1 , 1 , 0 ,1.25, 0 ,,,0.8,0,2,0,
WSPro=,,,, 1 ,,,, 0 ,,,, 0 ,,,,-1 ,-1 ,-1 , 0 , 0 , 0 , 0 , 0
BC Design=,, 0 ,, 0 ,,,,,,
BC HTab HWMax=2894.7

Type RM Length L Ch R = 1 ,6657    ,622,622,622
BEGIN DESCRIPTION:
XS29
END DESCRIPTION:
XS GIS Cut Line= 6
       801540.25       652220.08       801500.41       652124.33
       801377.02       651982.95       801319.83       651322.88
       801294.92       651252.99       801204.95       651227.29
#Sta/Elev= 30
  4109.3 2886.85  4125.5 2887.51  4158.2 2882.95    4196 2883.47    4213 2880.08
  4249.5 2876.55    4256 2876.92  4327.1 2871.75  4437.1 2869.44    4451 2867.89
  4464.5  2863.6  4464.6 2865.12  4477.1 2865.75  4635.8 2867.09    4710 2865.91
    4896 2868.66  4950.5 2868.34  4981.4 2866.95    4991    2865  4995.5 2863.24
  5004.5 2863.24    5009    2865  5015.6 2867.04  5088.7 2871.94  5100.6 2874.68
    5116 2876.44  5171.7 2877.64    5179 2881.47    5201 2886.89    5233 2889.69
#Mann= 4 ,-1 , 0
  4109.3     .05       0  4950.5    .045       0    4991     .04       0
    5009     .06       0
#XS Ineff= 3 ,-1
  4109.3 4764.97    2885    4765    4975    2865    5025    5233    2865
Permanent Ineff=
       F       F       F
Bank Sta=4991,5009
Exp/Cntr=0.5,0.3

Type RM Length L Ch R = 1 ,6035    ,568,568,568
BEGIN DESCRIPTION:
XS30
END DESCRIPTION:
XS GIS Cut Line= 6
       801746.13       652316.33        801809.9       652225.23
         801860.       651947.37       801869.11       651651.29
         801901.       651573.86       801937.44        651519.2
#Sta/Elev= 30
  4252.4 2877.44  4289.7 2875.56  4354.6 2870.08  4379.6 2863.47    4403 2861.52
  4420.8 2857.23  4438.1 2855.64  4482.9 2852.76  4563.4 2850.89    4599 2848.09
  4623.9 2847.93  4633.6 2848.91    4650 2847.83  4661.5 2846.94  4679.6 2848.25
  4732.8 2849.44  4901.1 2850.29  4943.3 2849.46  4965.2 2851.38  4974.9 2850.87
  4993.7 2848.77  4995.2 2846.94  5004.6 2846.94  5007.9 2848.78  5016.5 2850.86
  5035.9 2852.34  5037.8 2853.25  5052.8 2861.33  5080.2 2881.77  5091.6 2888.38
#Mann= 6 ,-1 , 0
  4252.4    .035       0    4650    .045       0  4974.9    .045       0
  4993.7     .04       0  5007.9    .045       0  5037.8     .09       0
#XS Ineff= 2 , 0
       0    4890    2855               0
Permanent Ineff=
       T       F
Bank Sta=4993.7,5007.9
Exp/Cntr=0.3,0.1

Type RM Length L Ch R = 1 ,5467    ,436,436,436
BEGIN DESCRIPTION:
XS30.5
END DESCRIPTION:
XS GIS Cut Line= 6
       801972.22       652351.78       802064.18       652251.95
       802161.39       652047.02       802216.56       651983.96
       802313.77        651939.3       802376.83       651792.17
#Sta/Elev= 30
  4513.4 2870.94  4531.2 2870.64  4538.6 2867.56  4553.8 2862.38  4557.7  2859.1
  4581.5 2858.82  4595.8 2854.98  4605.9 2853.47  4649.1 2849.61  4738.3 2845.57
  4801.3 2841.72  4867.5    2839  4928.5 2837.97  4957.6 2838.24  4963.7 2838.33
  4965.2 2836.28  4976.5 2832.44  4978.2  2832.7  4993.9 2835.13  4995.3 2832.17
  5004.7 2832.17  5012.6 2835.17  5023.9 2836.17    5036 2836.48  5100.7 2836.82
    5132 2836.51  5182.9 2835.71  5187.9 2837.03  5213.2 2850.98  5226.8 2857.24
#Mann= 6 ,-1 , 0
  4513.4    .035       0  4957.6    .045       0  4978.2     .05       0
  4993.9     .04       0  5012.6    .035       0    5132     .09       0
Bank Sta=4993.9,5012.6
Exp/Cntr=0.3,0.1

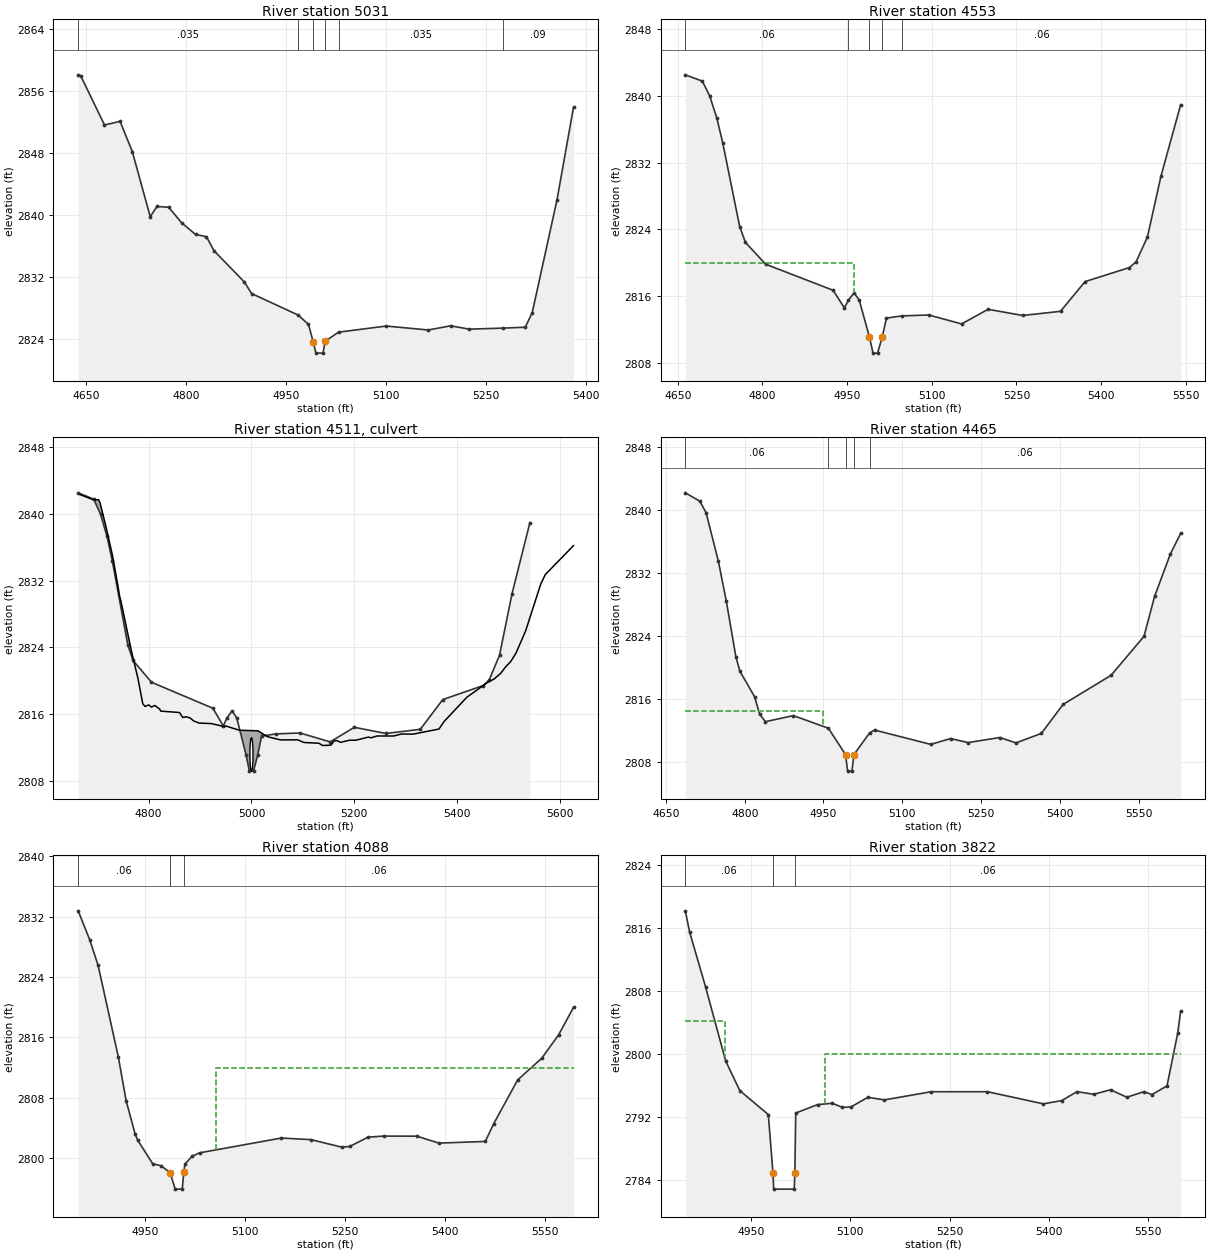
Type RM Length L Ch R = 1 ,5031    ,478,478,478
BEGIN DESCRIPTION:
XS31
END DESCRIPTION:
XS GIS Cut Line= 6
       802307.87       652523.86       802354.22       652398.72
       802504.86       652315.29       802574.38       652243.45
       802715.75       652044.14       802766.73       651965.35
#Sta/Elev= 30
  4637.7 2858.12  4641.4 2858.01  4677.2 2851.64  4700.6  2852.1    4719 2848.19
  4745.9 2839.78    4756 2841.11  4773.6    2841    4793    2839  4813.9 2837.49
  4830.3  2837.2  4841.7 2835.38  4887.3 2831.34  4898.1 2829.85  4967.8 2827.08
  4983.5 2825.87  4990.5 2823.64  4994.7 2822.15  5005.3 2822.15  5008.5 2823.67
  5028.6 2824.86  5100.4 2825.65  5163.4 2825.14  5196.9 2825.68  5224.8 2825.25
    5275 2825.38  5309.1  2825.5  5319.5 2827.38  5356.8    2842  5381.5 2853.94
#Mann= 6 ,-1 , 0
  4637.7    .035       0  4967.8    .045       0  4990.5     .04       0
  5008.5    .045       0  5028.6    .035       0    5275     .09       0
Bank Sta=4990.5,5008.5
Exp/Cntr=0.5,0.3

Type RM Length L Ch R = 1 ,4553    ,88,88,88
BEGIN DESCRIPTION:
XS31.7
END DESCRIPTION:
XS GIS Cut Line= 6
       802918.79       652813.21       802980.28        652726.1
       802925.36       652633.54       802931.64       652542.54
        803085.4       652180.11       803030.48       652010.67
#Sta/Elev= 30
  4663.3 2842.51  4693.5 2841.75  4706.8 2839.93  4719.3 2837.29  4729.6 2834.37
  4759.7 2824.31  4769.9 2822.43  4805.7 2819.82  4925.2  2816.7  4945.3 2814.58
  4952.3 2815.53  4962.4 2816.38  4971.5 2815.53  4989.6 2811.09    4996 2809.17
    5004 2809.17  5012.3 2811.13  5019.8 2813.37  5047.4 2813.63  5094.6 2813.74
  5152.9 2812.67  5199.9 2814.42  5261.3 2813.68  5328.2 2814.18  5371.8 2817.74
  5450.3 2819.42    5462 2820.09  5482.1 2823.05  5506.4 2830.42  5541.1 2838.93
#Mann= 5 ,-1 , 0
  4663.3     .06       0  4952.3    .045       0  4989.6     .04       0
  5012.3    .045       0  5047.4     .06       0
#XS Ineff= 2 , 0
       0  4962.4    2820    5046       0 2813.12
Permanent Ineff=
       F       F
Bank Sta=4989.6,5012.3
Exp/Cntr=0.5,0.3

Type RM Length L Ch R = 2 ,4511    ,,,
BEGIN DESCRIPTION:
XS32 TOR
Structure ID: XS32
Approximate Survey Structure
END DESCRIPTION:
Bridge Culvert--1,0,-1,-1, 0
Deck Dist Width WeirC Skew NumUp NumDn MinLoCord MaxHiCord MaxSubmerge Is_Ogee
33.5,32,3,0, 60, 60, , , , 0, 1,1,,
  4667.3  4692.5  4702.9  4705.7  4717.2  4730.3  4740.6  4743.5  4746.3  4767.4
  4779.2  4788.8  4793.1  4800.4  4805.8  4812.1  4821.8  4823.6  4860.2  4866.5
  4873.1  4881.1  4887.7  4898.3  4922.5    4948  4950.1  4976.3  5012.5    5031
  5056.3  5089.9    5102  5131.1  5138.4  5154.4  5160.6  5166.1  5173.3  5190.5
  5202.8  5227.3  5232.4  5244.3  5276.5  5291.8  5313.9  5364.4  5374.2  5418.4
  5459.9  5471.5  5484.8  5493.9  5503.8  5514.2  5532.9  5561.9  5570.8  5625.9
 2842.29 2841.68 2841.68 2841.33 2838.48  2834.9 2831.35 2830.21 2829.55 2823.39
 2820.35 2817.25 2816.92  2817.1 2816.84 2817.04  2816.6 2816.36 2816.19  2815.6
 2815.68 2815.53 2815.18 2814.93 2814.86 2814.49 2814.58 2814.07    2814  2813.3
 2812.91 2812.92  2812.6 2812.51 2812.24 2812.28 2812.79 2812.82 2812.62 2812.87
 2812.87 2813.25 2813.16 2813.38 2813.38 2813.62  2813.6 2814.21  2815.1 2818.01
 2819.84  2820.2 2820.91 2821.66 2822.29 2823.32 2825.98 2831.52  2832.7 2836.19
    2788    2788    2788    2788    2788    2788    2788    2788    2788    2788
    2788    2788    2788    2788    2788    2788    2788    2788    2788    2788
    2788    2788    2788    2788    2788    2788    2788    2788    2788    2788
    2788    2788    2788    2788    2788    2788    2788    2788    2788    2788
    2788    2788    2788    2788    2788    2788    2788    2788    2788    2788
    2788    2788    2788    2788    2788    2788    2788    2788    2788    2788
  4667.3  4692.5  4702.9  4705.7  4717.2  4730.3  4740.6  4743.5  4746.3  4767.4
  4779.2  4788.8  4793.1  4800.4  4805.8  4812.1  4821.8  4823.6  4860.2  4866.5
  4873.1  4881.1  4887.7  4898.3  4922.5    4948  4950.1  4976.3  5012.5    5031
  5056.3  5089.9    5102  5131.1  5138.4  5154.4  5160.6  5166.1  5173.3  5190.5
  5202.8  5227.3  5232.4  5244.3  5276.5  5291.8  5313.9  5364.4  5374.2  5418.4
  5459.9  5471.5  5484.8  5493.9  5503.8  5514.2  5532.9  5561.9  5570.8  5625.9
 2842.29 2841.68 2841.68 2841.33 2838.48  2834.9 2831.35 2830.21 2829.55 2823.39
 2820.35 2817.25 2816.92  2817.1 2816.84 2817.04  2816.6 2816.36 2816.19  2815.6
 2815.68 2815.53 2815.18 2814.93 2814.86 2814.49 2814.58 2814.07    2814  2813.3
 2812.91 2812.92  2812.6 2812.51 2812.24 2812.28 2812.79 2812.82 2812.62 2812.87
 2812.87 2813.25 2813.16 2813.38 2813.38 2813.62  2813.6 2814.21  2815.1 2818.01
 2819.84  2820.2 2820.91 2821.66 2822.29 2823.32 2825.98 2831.52  2832.7 2836.19
    2788    2788    2788    2788    2788    2788    2788    2788    2788    2788
    2788    2788    2788    2788    2788    2788    2788    2788    2788    2788
    2788    2788    2788    2788    2788    2788    2788    2788    2788    2788
    2788    2788    2788    2788    2788    2788    2788    2788    2788    2788
    2788    2788    2788    2788    2788    2788    2788    2788    2788    2788
    2788    2788    2788    2788    2788    2788    2788    2788    2788    2788
BR Coef= 1 , 1 , 0 ,1.25, 0 ,,,0.8,0,2,0,
WSPro=,,,, 1 ,,,, 0 ,,,, 0 ,,,,-1 ,-1 ,-1 , 0 , 0 , 0 , 0 , 0
Culvert=5,4,6,32,0.027,0.9,1,41,3,2809.17,5000,2806.9,5000,Culvert #1  , 0 ,33.5
Culvert Bottom n=0.027
BC Design=,, 0 ,, 0 ,,,,,,
BC HTab HWMax=2842.54

Type RM Length L Ch R = 1 ,4465    ,377,377,377
BEGIN DESCRIPTION:
XS32.2
END DESCRIPTION:
XS GIS Cut Line= 6
       802987.38       652846.01       803054.02       652711.98
       803005.38       652589.61       803151.29       652335.44
       803195.22       652136.18       803173.26       651974.74
#Sta/Elev= 30
  4686.9 2842.19  4714.5 2841.13  4726.5 2839.66  4749.9  2833.5  4764.8 2828.52
  4783.1 2821.42  4790.9 2819.56  4818.8 2816.34  4828.4 2814.13  4839.5 2813.17
  4892.5 2813.94  4959.4 2812.34    4992    2809    4996  2806.9  5004.2  2806.9
    5008    2809  5038.1 2811.77  5047.2 2812.11  5154.4 2810.29    5192 2811.03
  5225.4 2810.52  5285.7 2811.16  5316.7 2810.48  5364.9 2811.68  5406.4 2815.36
  5497.7 2819.05  5560.4 2823.99  5580.6 2829.06  5610.7 2834.45  5630.2 2837.05
#Mann= 5 ,-1 , 0
  4686.9     .06       0  4959.4    .045       0    4992     .04       0
    5008    .045       0  5038.1     .06       0
#XS Ineff= 2 , 0
       0    4950 2814.58    5050       0    2812
Permanent Ineff=
       F       F
Bank Sta=4992,5008
Exp/Cntr=0.5,0.3

Type RM Length L Ch R = 1 ,4088    ,266,266,266
BEGIN DESCRIPTION:
z15
END DESCRIPTION:
XS GIS Cut Line= 3
       803258.73       652890.99        803331.7       652761.53
       803531.77       652201.32
#Sta/Elev= 30
  4849.1 2832.79  4866.3 2828.98    4879 2825.56  4909.4 2813.41  4921.1  2807.6
  4934.6 2803.21  4938.4 2802.39  4960.9 2799.27  4973.7    2799  4987.2 2798.06
  4994.7  2795.9  5005.3  2795.9  5007.6 2798.16  5009.3 2799.22  5020.4 2800.27
  5031.2 2800.71    5154 2802.67  5198.7 2802.46  5244.8 2801.46  5256.6 2801.56
  5284.3 2802.79  5307.6 2802.93  5357.3 2802.92  5390.5    2802  5460.2 2802.22
  5472.9 2804.59  5508.8 2810.38  5544.9 2813.25  5570.1 2816.33  5592.6 2819.99
#Mann= 3 , 0 , 0
  4849.1     .06       0  4987.2     .04       0  5007.6     .06       0
#XS Ineff= 2 , 0
       0                  5055.8       0    2812
Permanent Ineff=
       F       T
Bank Sta=4987.2,5007.6
Exp/Cntr=0.5,0.3

Type RM Length L Ch R = 1 ,3822    ,144,144,144
BEGIN DESCRIPTION:
XS33
END DESCRIPTION:
XS GIS Cut Line= 5
       803473.56       653049.92       803538.44       652950.27
        803549.1       652879.08       803699.74       652541.64
       803767.53       652366.89
#Sta/Elev= 30
  4851.1  2818.2  4857.6  2815.5  4881.6 2808.55  4912.1 2799.09  4933.3 2795.34
  4976.4 2792.28  4983.5  2784.8  4984.5  2782.8  5015.5  2782.8  5016.5  2784.8
  5017.8 2792.48  5050.8 2793.55  5072.9 2793.72  5088.4  2793.2  5101.4 2793.26
  5126.7 2794.48  5151.7 2794.15  5222.4 2795.19  5307.3 2795.19  5391.6 2793.65
  5419.4 2794.06  5442.6  2795.2  5467.7 2794.86  5493.1 2795.44  5517.8 2794.49
  5543.7  2795.2  5555.6 2794.82  5578.4 2795.93  5594.5 2802.62    5599 2805.45
#Mann= 3 ,-1 , 0
  4851.1     .06       0  4983.5     .04       0  5016.5     .06       0
#XS Ineff= 2 , 0
       0  4910.5 2804.24    5062       0    2800
Permanent Ineff=
       F       T
Bank Sta=4983.5,5016.5
Exp/Cntr=0.5,0.3