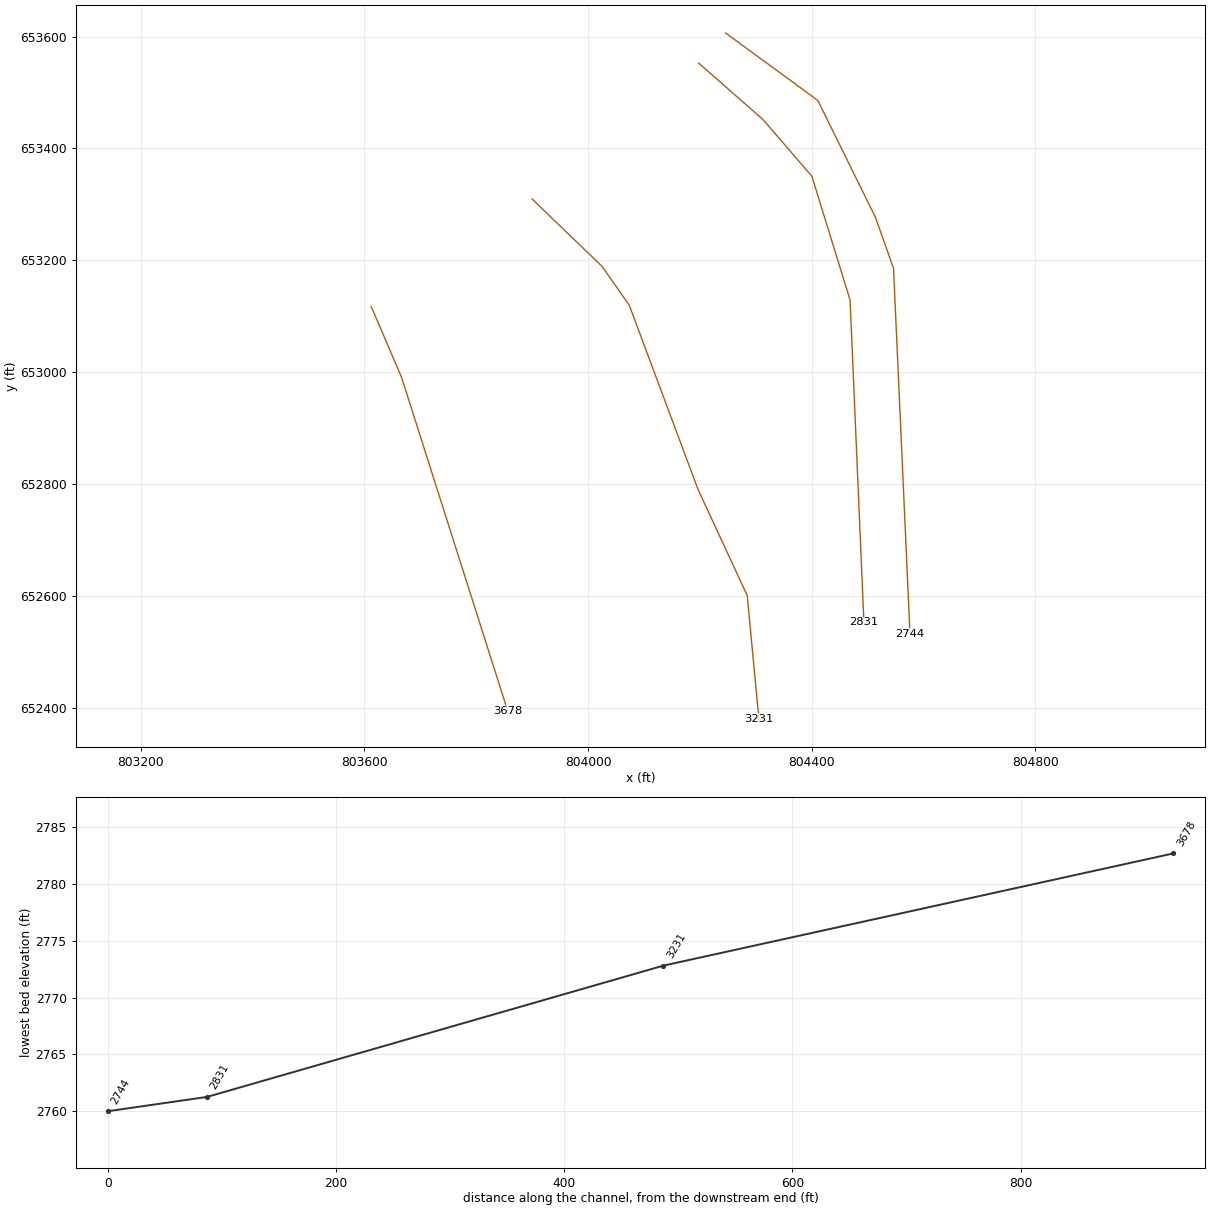
HEC-RAS study lds_plott_crk.prj: Plott Creek Limited Detail Study

--- lds_plott_crk.g01 (geometry) --- (continued)

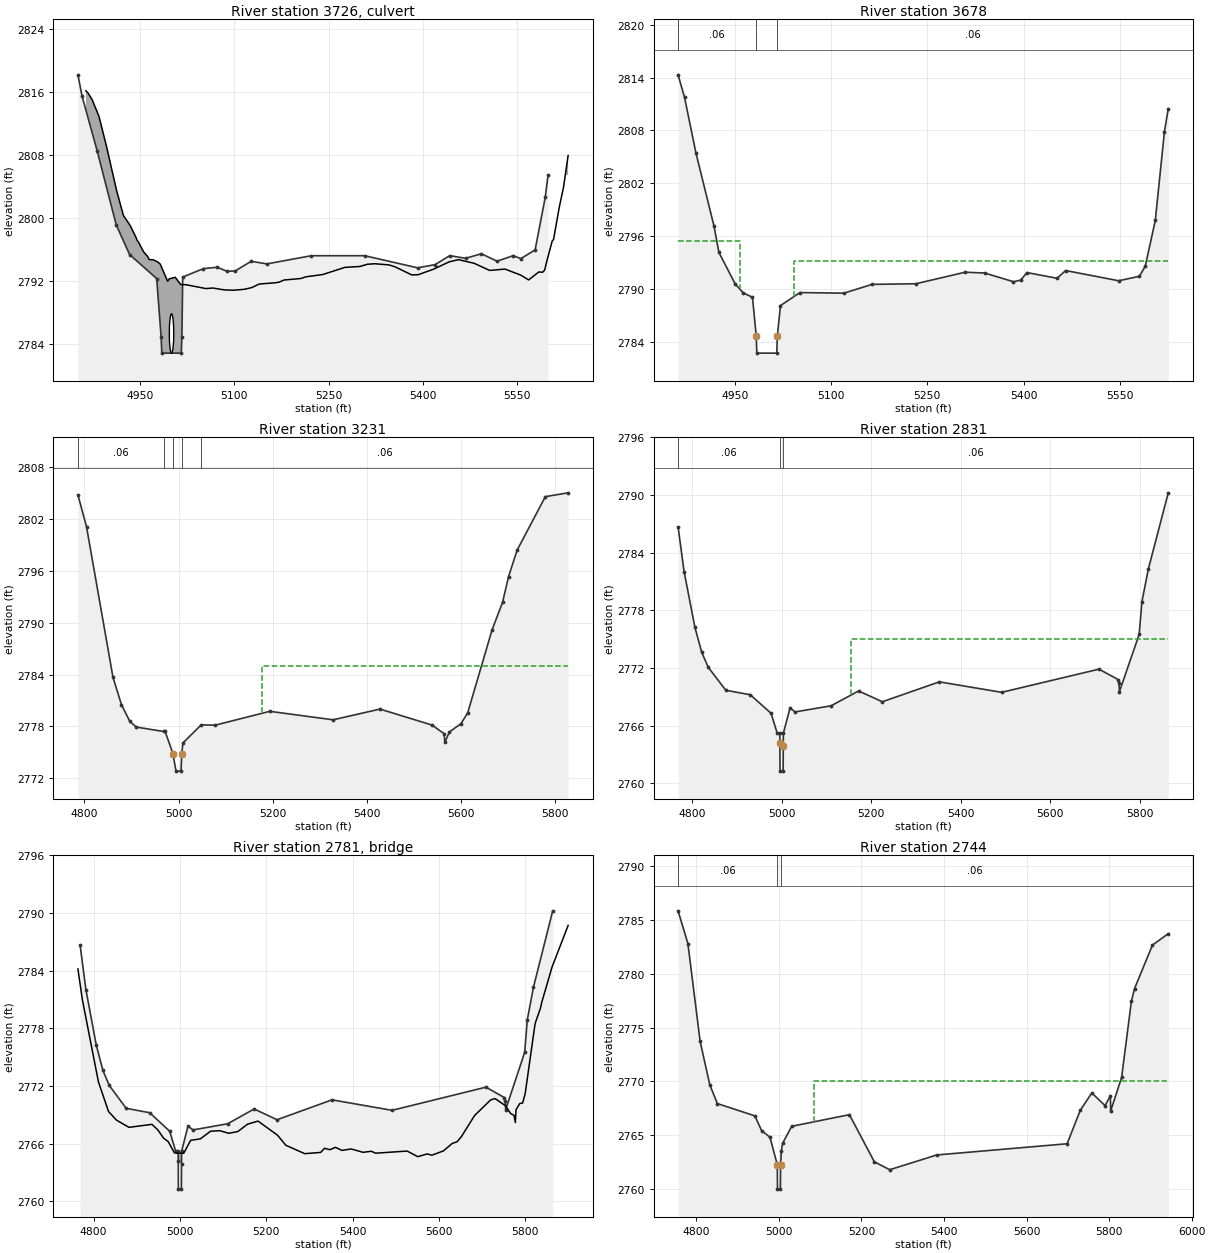
Type RM Length L Ch R = 2 ,3726    ,,,
BEGIN DESCRIPTION:
z10_tor
Structure ID: 1416 potts creek rd
Approximate Survey Structure
END DESCRIPTION:
Bridge Culvert--1,0,-1,-1, 0
Deck Dist Width WeirC Skew NumUp NumDn MinLoCord MaxHiCord MaxSubmerge Is_Ogee
86,20,3,0, 60, 60, , , , 0, 1,1,,
  4863.8    4867  4873.5  4884.5  4896.8  4912.6  4923.4  4934.3  4944.2  4944.9
  4947.2  4955.5    4962  4964.5  4970.6  4977.8    4982  4993.8  4996.4  5005.8
  5014.6  5023.1  5054.7    5066  5084.2  5098.7    5116  5127.8  5139.6    5165
  5171.3    5179  5205.6  5214.1  5240.7  5275.9  5299.6  5311.3  5323.2  5346.1
  5355.5  5382.1  5392.1  5416.7  5441.6  5456.5  5481.3  5506.1  5530.6  5555.9
    5568  5584.2  5590.5  5593.6  5596.8  5605.7  5607.7  5616.8  5623.6  5630.9
 2816.17  2815.9 2815.08 2812.94 2809.02 2803.49 2800.33 2799.02  2797.4 2797.18
 2796.95 2795.69 2795.09  2794.7 2794.68 2794.41 2794.13 2791.94 2792.25 2792.45
 2791.53  2791.5 2791.01 2791.08 2790.84  2790.8 2790.92 2791.14 2791.59 2791.75
 2791.83  2792.1 2792.29 2792.51  2792.8 2793.71 2793.82  2794.1 2794.17 2794.02
 2793.78 2792.75 2792.77 2793.47 2794.41 2794.69 2794.23 2793.32 2793.49 2792.71
 2792.11 2793.12 2793.09 2793.37 2794.44 2797.09 2797.24 2801.35 2803.91 2807.94
  2762.8  2762.8  2762.8  2762.8  2762.8  2762.8  2762.8  2762.8  2762.8  2762.8
  2762.8  2762.8  2762.8  2762.8  2762.8  2762.8  2762.8  2762.8  2762.8  2762.8
  2762.8  2762.8  2762.8  2762.8  2762.8  2762.8  2762.8  2762.8  2762.8  2762.8
  2762.8  2762.8  2762.8  2762.8  2762.8  2762.8  2762.8  2762.8  2762.8  2762.8
  2762.8  2762.8  2762.8  2762.8  2762.8  2762.8  2762.8  2762.8  2762.8  2762.8
  2762.8  2762.8  2762.8  2762.8  2762.8  2762.8  2762.8  2762.8  2762.8  2762.8
  4863.8    4867  4873.5  4884.5  4896.8  4912.6  4923.4  4934.3  4944.2  4944.9
  4947.2  4955.5    4962  4964.5  4970.6  4977.8    4982  4993.8  4996.4  5005.9
  5014.6  5023.1  5054.7    5066  5084.2  5098.7    5116  5127.8  5139.6    5165
  5171.3    5179  5205.6  5214.1  5240.7  5275.9  5299.6  5311.3  5323.2  5346.1
  5355.5  5382.1  5392.1  5416.7  5441.6  5456.5  5481.3  5506.1  5530.6  5555.9
    5568  5584.2  5590.5  5593.6  5596.8  5605.7  5607.7  5616.8  5623.6  5630.9
 2816.17  2815.9 2815.08 2812.94 2809.02 2803.49 2800.33 2799.02  2797.4 2797.18
 2796.95 2795.69 2795.09  2794.7 2794.68 2794.41 2794.13 2791.94 2792.25 2792.46
 2791.53  2791.5 2791.01 2791.08 2790.84  2790.8 2790.92 2791.14 2791.59 2791.75
 2791.83  2792.1 2792.29 2792.51  2792.8 2793.71 2793.82  2794.1 2794.17 2794.02
 2793.78 2792.75 2792.77 2793.47 2794.41 2794.69 2794.23 2793.32 2793.49 2792.71
 2792.11 2793.12 2793.09 2793.37 2794.44 2797.09 2797.24 2801.35 2803.91 2807.94
  2762.7  2762.7  2762.7  2762.7  2762.7  2762.7  2762.7  2762.7  2762.7  2762.7
  2762.7  2762.7  2762.7  2762.7  2762.7  2762.7  2762.7  2762.7  2762.7  2762.7
  2762.7  2762.7  2762.7  2762.7  2762.7  2762.7  2762.7  2762.7  2762.7  2762.7
  2762.7  2762.7  2762.7  2762.7  2762.7  2762.7  2762.7  2762.7  2762.7  2762.7
  2762.7  2762.7  2762.7  2762.7  2762.7  2762.7  2762.7  2762.7  2762.7  2762.7
  2762.7  2762.7  2762.7  2762.7  2762.7  2762.7  2762.7  2762.7  2762.7  2762.7
Culvert=5,5,7,20,0.027,0.5,1,41,1,2782.8,5000,2782.7,5000,Culvert #1  , 0 ,86
Culvert Bottom n=0.027
BC Design=,, 0 ,, 0 ,,,,,,
BC HTab HWMax=2818.2

Type RM Length L Ch R = 1 ,3678    ,447,447,447
BEGIN DESCRIPTION:
z11
END DESCRIPTION:
XS GIS Cut Line= 3
       803612.37       653117.09        803666.6       652990.55
       803856.41       652394.01
#Sta/Elev= 30
  4861.8 2814.31  4871.9 2811.74  4889.6 2805.44  4917.9 2797.09  4925.4 2794.14
  4950.9 2790.54  4963.3 2789.55  4977.7 2789.04  4983.5  2784.7  4984.5  2782.7
  5015.5  2782.7  5016.5  2784.7  5021.3  2788.1  5051.7 2789.58  5120.1 2789.51
  5164.1 2790.51  5232.2 2790.58    5309 2791.89  5339.4  2791.8  5384.2 2790.81
  5395.5 2790.99  5405.3 2791.85  5452.3  2791.2  5465.5 2792.08  5548.1 2790.92
  5580.5 2791.43  5589.6 2792.58  5605.2 2797.77  5619.4 2807.83  5625.4 2810.45
#Mann= 3 ,-1 , 0
  4861.8     .06       0  4983.5     .04       0  5016.5     .06       0
#XS Ineff= 2 , 0
       0  4958.5 2795.41 5041.63       0  2793.2
Permanent Ineff=
       F       F
Bank Sta=4983.5,5016.5
Exp/Cntr=0.5,0.3

Type RM Length L Ch R = 1 ,3231    ,400,400,400
BEGIN DESCRIPTION:
XS34
END DESCRIPTION:
XS GIS Cut Line= 6
       803899.97       653309.48       804025.11       653188.97
       804073.78       653119.44        804196.6       652790.37
       804284.67       652600.33       804305.52       652380.18
#Sta/Elev= 30
  4786.5 2804.79  4804.7 2801.12  4860.9 2783.68  4878.8 2780.53  4896.7 2778.57
  4910.3 2777.92  4968.3 2777.41  4971.3 2777.46  4988.1 2774.85  4994.7 2772.82
  5005.3 2772.82  5006.9 2774.85  5009.4 2776.08  5048.1 2778.17  5077.9 2778.14
  5193.8 2779.74  5328.1 2778.76  5427.7    2780  5538.2 2778.15  5563.9 2777.15
  5565.3 2776.15    5575 2777.35  5599.9 2778.33    5614 2779.59  5665.4 2789.14
  5687.9 2792.37  5700.5 2795.32  5718.7 2798.39  5778.7 2804.59    5827 2805.03
#Mann= 5 ,-1 , 0
  4786.5     .06       0  4968.3    .045       0  4988.1     .04       0
  5006.9    .045       0  5048.1     .06       0
#XS Ineff= 2 , 0
       0                 5177.91       0    2785
Permanent Ineff=
       F       T
Bank Sta=4988.1,5006.9
Exp/Cntr=0.3,0.1

Type RM Length L Ch R = 1 ,2831    ,87,87,87
BEGIN DESCRIPTION:
z20
END DESCRIPTION:
XS GIS Cut Line= 5
        804197.9       653552.41       804313.24       653451.19
       804400.33       653349.98       804468.59       653128.72
        804493.3       652552.92
#Sta/Elev= 30
  4768.8 2786.68  4782.3 2782.02  4806.2 2776.27  4821.6 2773.62  4836.4 2772.05
  4875.6 2769.67    4930 2769.21  4976.5 2767.28  4990.3  2765.2    4996  2765.2
 4996.26 2764.19  4996.5 2761.26  5003.5 2761.26 5003.82 2763.86    5004  2765.2
  5018.8 2767.82  5030.4 2767.42  5110.6 2768.06    5172  2769.6  5225.1 2768.48
  5352.4 2770.55  5491.5 2769.46    5709 2771.87  5751.7 2770.79  5753.6 2770.45
  5754.7 2769.54  5798.7 2775.48  5804.8 2778.87  5819.1 2782.27  5863.7 2790.22
#Mann= 3 , 0 , 0
  4768.8     .06       0 4996.26     .04       0 5003.82     .06       0
#XS Ineff= 3 ,-1
  4768.8    4948 2767.46  5050.5  5153.1 2767.46    5154  5863.7    2775
Permanent Ineff=
       F       F       F
Bank Sta=4996.26,5003.82
Exp/Cntr=0.5,0.3

Type RM Length L Ch R = 3 ,2781    ,,,
BEGIN DESCRIPTION:
XS34.5
Structure ID: road off of plot creek
Approximate Survey Structure
END DESCRIPTION:
Bridge Culvert--1,0,-1,-1, 0
Deck Dist Width WeirC Skew NumUp NumDn MinLoCord MaxHiCord MaxSubmerge Is_Ogee
43,14,3,0, 60, 60, , , , 0, 1,1,,
  4763.8  4774.1  4811.3  4834.6  4853.1    4882  4935.3  4948.8  4962.3    4973
  4987.3    4991    4991    5009    5009    5025  5047.5  5071.2  5092.5  5113.3
  5134.2  5156.8  5181.1  5226.2  5245.5  5289.3  5326.2  5335.1  5347.6  5360.4
  5375.6  5396.9  5424.4  5443.6  5453.2  5526.5  5551.1  5572.8  5583.7  5610.7
  5630.7  5642.2  5652.7  5682.7  5720.1  5730.3  5754.5  5766.1    5774  5777.2
  5778.6  5787.4    5794  5799.9  5822.5  5824.1  5835.2  5838.6  5862.1  5899.4
 2784.17 2780.97 2772.42 2769.34 2768.44 2767.69    2768 2767.43 2766.56  2766.2
 2765.04    2765    2765    2765    2765 2766.34 2766.49 2767.29 2767.34 2767.07
 2767.25 2768.02 2768.34 2766.87 2765.82 2764.95 2765.08 2765.51 2765.36 2765.61
 2765.29 2765.44 2765.09  2765.2    2765 2765.22 2764.64 2764.92 2764.79 2765.24
 2766.01 2766.19 2766.76 2768.92 2770.55 2770.68 2769.93 2769.13 2768.94 2768.19
 2769.51 2770.17 2770.22 2771.19 2778.36 2778.65 2780.07 2780.74 2784.36  2788.7
  2737.7  2737.7  2737.7  2737.7  2737.7  2737.7  2737.7  2737.7  2737.7  2737.7
  2737.7  2737.7    2764    2764  2737.7  2737.7  2737.7  2737.7  2737.7  2737.7
  2737.7  2737.7  2737.7  2737.7  2737.7  2737.7  2737.7  2737.7  2737.7  2737.7
  2737.7  2737.7  2737.7  2737.7  2737.7  2737.7  2737.7  2737.7  2737.7  2737.7
  2737.7  2737.7  2737.7  2737.7  2737.7  2737.7  2737.7  2737.7  2737.7  2737.7
  2737.7  2737.7  2737.7  2737.7  2737.7  2737.7  2737.7  2737.7  2737.7  2737.7
  4763.8  4774.1  4811.3  4834.6  4853.1    4882  4935.3  4948.8  4962.3    4973
  4987.3    4991    4991    5009    5009    5025  5047.5  5071.2  5092.5  5113.3
  5134.2  5156.8  5181.1  5226.2  5245.5  5289.3  5326.2  5335.1  5347.6  5360.4
  5375.6  5396.9  5424.4  5443.6  5453.2  5526.5  5551.1  5572.8  5583.7  5610.7
  5630.7  5642.2  5652.7  5682.7  5720.1  5730.3  5754.5  5766.1    5774  5777.2
  5778.6  5787.4    5794  5799.9  5822.5  5824.1  5835.2  5838.6  5862.1  5899.4
 2784.17 2780.97 2772.42 2769.34 2768.44 2767.69    2768 2767.43 2766.56  2766.2
 2765.04    2765    2765    2765    2765 2766.34 2766.49 2767.29 2767.34 2767.07
 2767.25 2768.02 2768.34 2766.87 2765.82 2764.95 2765.08 2765.51 2765.36 2765.61
 2765.29 2765.44 2765.09  2765.2    2765 2765.22 2764.64 2764.92 2764.79 2765.24
 2766.01 2766.19 2766.76 2768.92 2770.55 2770.68 2769.93 2769.13 2768.94 2768.19
 2769.51 2770.17 2770.22 2771.19 2778.36 2778.65 2780.07 2780.74 2784.36  2788.7
  2737.7  2737.7  2737.7  2737.7  2737.7  2737.7  2737.7  2737.7  2737.7  2737.7
  2737.7  2737.7    2764    2764  2737.7  2737.7  2737.7  2737.7  2737.7  2737.7
  2737.7  2737.7  2737.7  2737.7  2737.7  2737.7  2737.7  2737.7  2737.7  2737.7
  2737.7  2737.7  2737.7  2737.7  2737.7  2737.7  2737.7  2737.7  2737.7  2737.7
  2737.7  2737.7  2737.7  2737.7  2737.7  2737.7  2737.7  2737.7  2737.7  2737.7
  2737.7  2737.7  2737.7  2737.7  2737.7  2737.7  2737.7  2737.7  2737.7  2737.7
Abutment Skew #Up #Dn= , 2 , 2
    4991    4992
    2762 2763.26
    4991    4992
    2762 2762.56
Abutment Skew #Up #Dn= , 2 , 2
    5008    5009
 2762.28    2762
    5008    5009
 2764.04    2762
BR Coef= 1 , 1 , 0 ,1.25, 0 ,,,0.8,0,2,0,
WSPro=,,,, 1 ,,,, 0 ,,,, 0 ,,,,-1 ,-1 ,-1 , 0 , 0 , 0 , 0 , 0
BC Design=,, 0 ,, 0 ,,,,,,
BC HTab HWMax=2790.22

Type RM Length L Ch R = 1 ,2744    ,345,345,345
BEGIN DESCRIPTION:
z21
END DESCRIPTION:
XS GIS Cut Line= 5
       804246.15       653606.25       804410.92       653485.62
        804513.9       653276.72       804546.26       653185.51
       804575.69       652532.33
#Sta/Elev= 30
  4755.6 2785.83  4779.4 2782.79    4809 2773.72  4832.5 2769.68  4850.8 2767.94
  4941.7  2766.8  4957.9 2765.44  4978.3 2764.81    4996 2762.26  4996.5    2760
  5003.5    2760    5004 2762.26  5005.9 2763.56  5008.9 2764.25  5030.9 2765.83
  5170.7 2766.91  5231.1 2762.54  5268.4  2761.8  5382.3 2763.17  5698.2 2764.21
  5730.2 2767.32  5758.1 2768.93  5790.1 2767.75  5803.1 2768.66  5803.8 2767.26
  5830.3 2770.37  5853.9 2777.42  5861.7 2778.62    5905 2782.65  5943.3 2783.71
#Mann= 3 ,-1 , 0
  4755.6     .06       0    4996     .05       0    5004     .06       0
#XS Ineff= 3 ,-1
  4755.6    4970    2764  5042.5  5084.5    2764    5085  5939.2    2770
Permanent Ineff=
       F       F       F
Bank Sta=4996,5004
Exp/Cntr=0.5,0.3