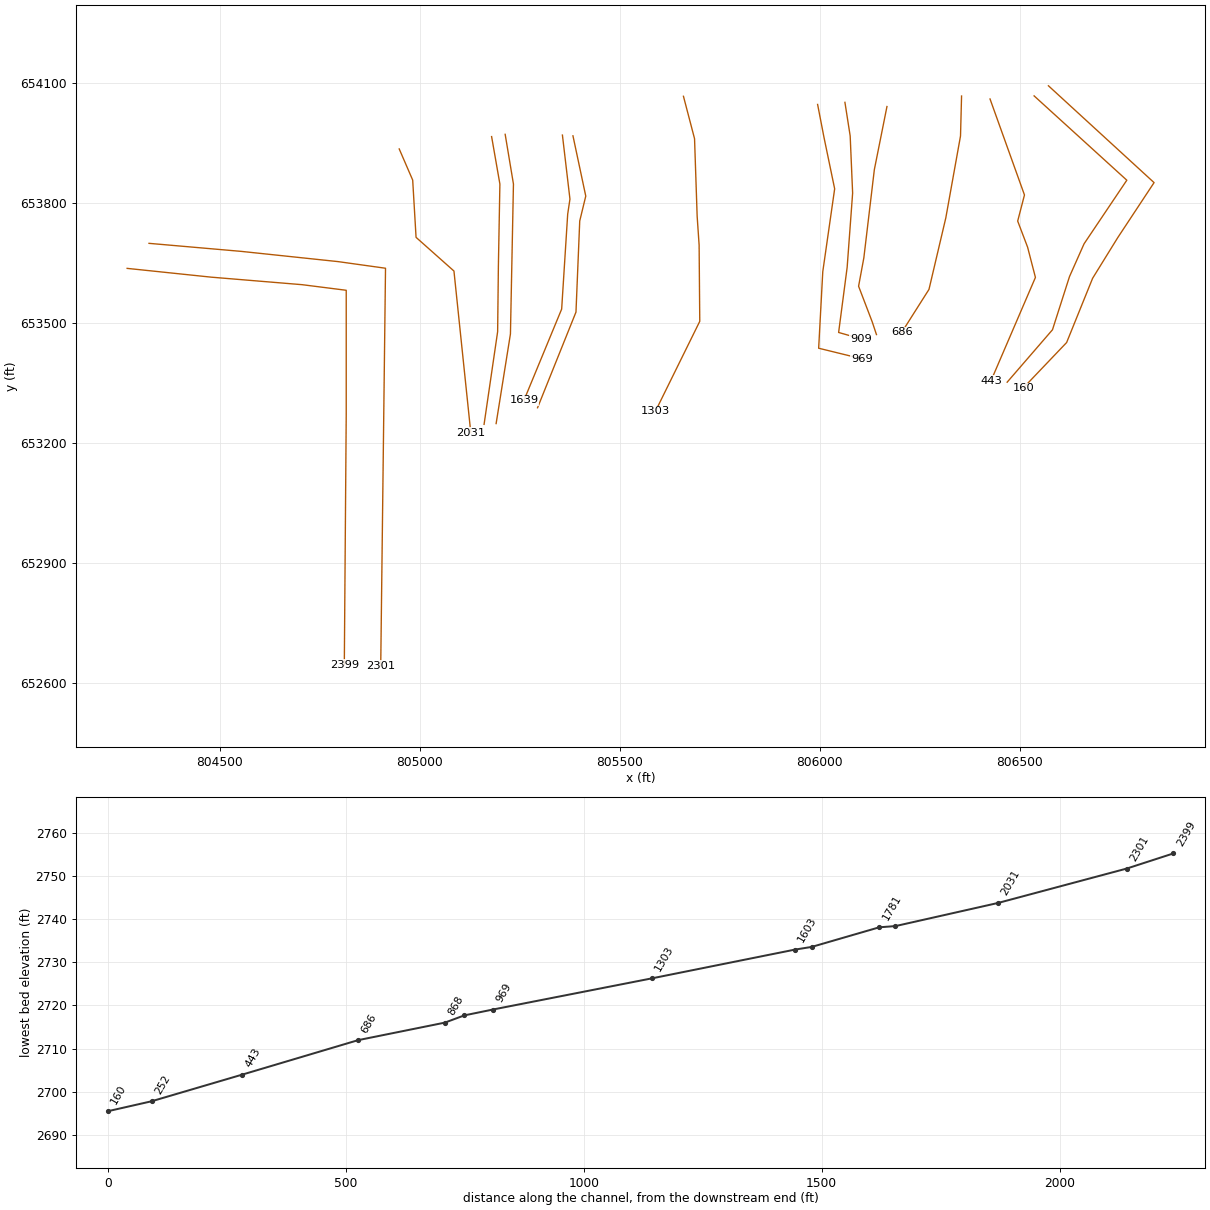
HEC-RAS study lds_plott_crk.prj: Plott Creek Limited Detail Study

--- lds_plott_crk.g01 (geometry) --- (continued)

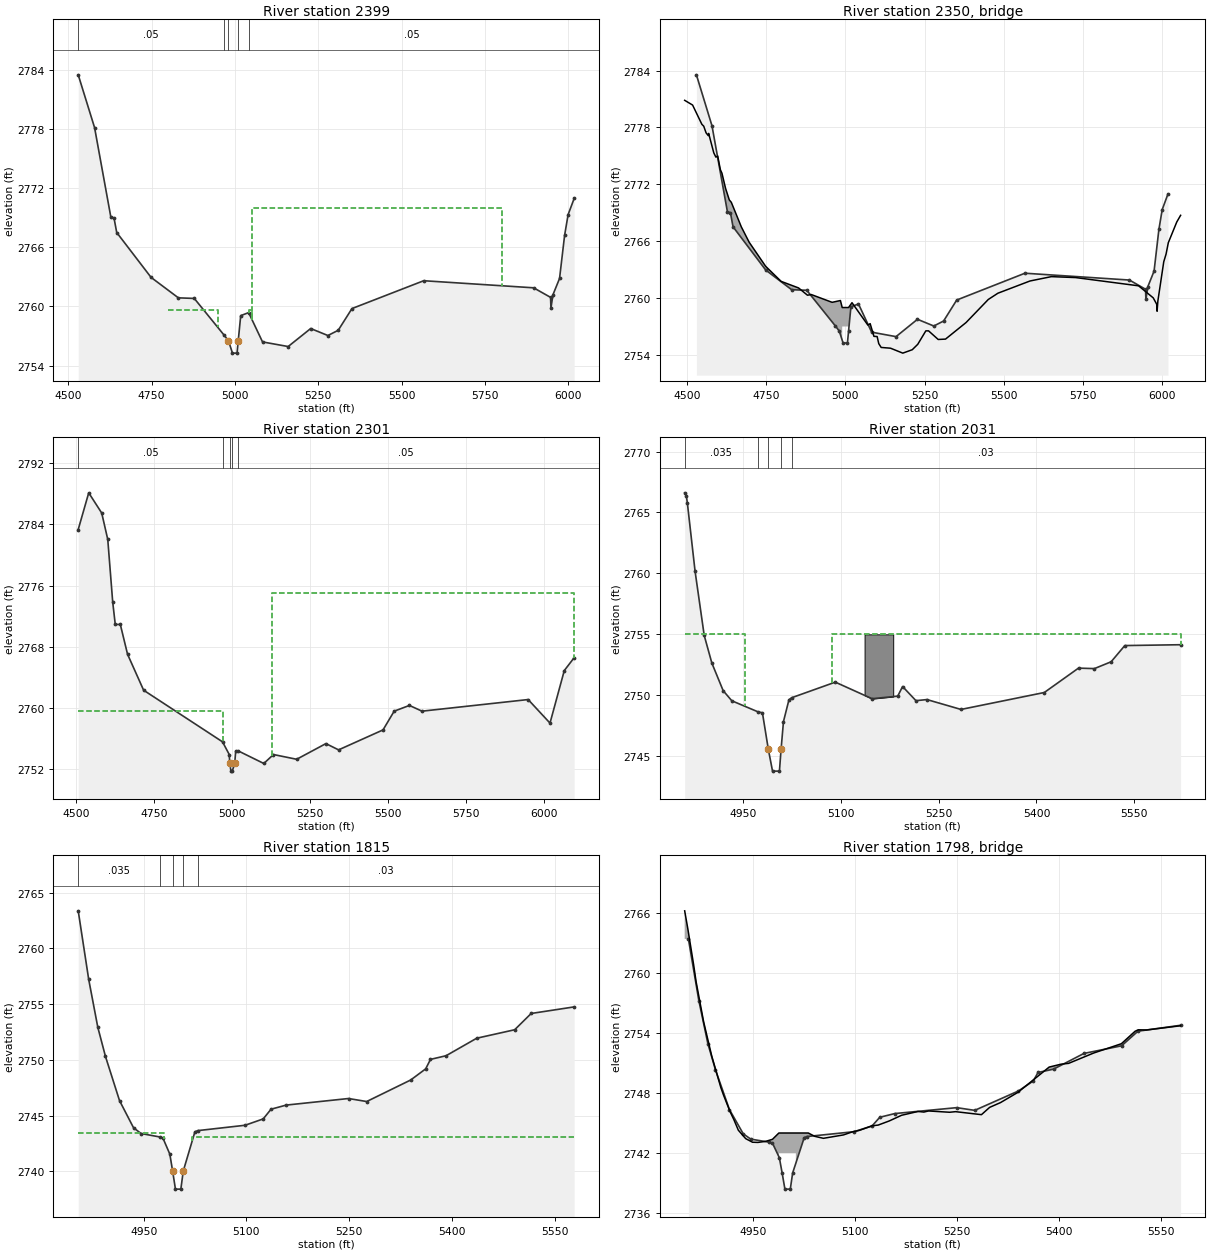
Type RM Length L Ch R = 1 ,2399    ,98,98,98
BEGIN DESCRIPTION:
XS35
END DESCRIPTION:
XS GIS Cut Line= 6
       804268.21       653636.51       804478.45       653614.54
       804705.95       653595.71       804816.02       653581.74
       804816.02       653272.65       804811.22       652644.88
#Sta/Elev= 30
  4530.1 2783.55  4579.2 2778.18  4627.8 2769.12  4637.5 2768.99  4645.6 2767.52
  4748.6 2762.96  4830.5 2760.88  4878.2 2760.82  4967.4  2757.1  4980.7 2756.52
  4992.8 2755.26  5006.5 2755.26    5010 2756.49  5017.5 2759.07  5041.3 2759.38
  5082.9  2756.4  5159.8 2755.93  5227.4 2757.76    5279 2757.05  5309.9 2757.58
  5351.2 2759.79  5566.4 2762.62    5896  2761.9  5946.8 2760.93    5948 2759.85
    5954 2761.19  5973.8 2762.85    5989 2767.24  5999.5 2769.34  6017.6 2770.98
#Mann= 5 ,-1 , 0
  4530.1     .05       0  4967.4    .045       0  4980.7     .04       0
    5010    .045       0  5041.3     .05       0
#XS Ineff= 3 ,-1
    4800  4948.5 2759.65    5042    5051 2759.65  5051.5    5800    2770
Permanent Ineff=
       F       F       F
Bank Sta=4980.7,5010
Exp/Cntr=0.5,0.3

Type RM Length L Ch R = 3 ,2350    ,,,
BEGIN DESCRIPTION:
XS36 TOR
Structure ID: XS36
Approximate Survey Structure
END DESCRIPTION:
Bridge Culvert--1,0,-1,-1, 0
Deck Dist Width WeirC Skew NumUp NumDn MinLoCord MaxHiCord MaxSubmerge Is_Ogee
39,20,3,0, 60, 60, , , , 0, 1,1,,
  4493.1  4518.1  4547.3  4553.2  4560.6  4567.4  4568.7  4584.9  4591.5  4597.3
  4605.7  4610.7  4622.1  4633.9  4640.2  4671.9  4696.5  4748.5  4797.3  4852.2
  4880.4  4892.4  4958.2  4984.4    4990    4990    5010    5010  5020.9  5070.9
  5078.2  5090.1  5100.2  5105.3  5112.9  5142.4  5181.1    5211  5228.3  5253.8
  5262.4  5292.8  5315.9  5380.8  5450.8  5481.1  5582.3  5649.8  5726.6    5925
  5971.1  5981.4  5983.1  5983.3  5985.7  6004.3  6011.6  6018.7  6045.3  6057.5
 2780.86 2780.36 2778.33 2778.13 2777.43 2777.14 2777.37 2775.32 2774.87 2774.98
 2773.54 2773.17 2771.57 2770.35  2770.1  2767.5 2765.89 2763.35 2761.76 2761.07
  2760.3 2760.37 2759.55 2759.74    2759    2759    2759    2759 2759.51 2757.15
  2757.3 2755.96 2755.94 2755.19 2754.79 2754.71 2754.19 2754.55 2755.12 2756.54
 2756.54 2755.63 2755.67 2757.42 2759.85 2760.51  2761.8 2762.26 2762.16 2761.29
 2760.02 2759.39 2759.17 2758.61 2759.68 2763.83 2764.64 2765.84 2768.02 2768.73
    2732    2732    2732    2732    2732    2732    2732    2732    2732    2732
    2732    2732    2732    2732    2732    2732    2732    2732    2732    2732
    2732    2732    2732    2732    2732    2757    2757    2732    2732    2732
    2732    2732    2732    2732    2732    2732    2732    2732    2732    2732
    2732    2732    2732    2732    2732    2732    2732    2732    2732    2732
    2732    2732    2732    2732    2732    2732    2732    2732    2732    2732
  4493.1  4518.1  4547.3  4553.2  4560.6  4567.4  4568.7  4584.9  4591.5  4597.3
  4605.7  4610.7  4622.1  4633.9  4640.2  4671.9  4696.5  4748.5  4797.3  4852.2
  4880.4  4892.4  4958.2  4984.4    4990    4990    5010    5010  5020.9  5070.9
  5078.2  5090.1  5100.2  5105.3  5112.9  5142.4  5181.1    5211  5228.3  5253.8
  5262.4  5292.8  5315.9  5380.8  5450.8  5481.1  5582.3  5649.8  5726.6    5925
  5971.1  5981.4  5983.1  5983.3  5985.7  6004.3  6011.6  6018.7  6045.3  6057.5
 2780.86 2780.36 2778.33 2778.13 2777.43 2777.14 2777.37 2775.32 2774.87 2774.98
 2773.54 2773.17 2771.57 2770.35  2770.1  2767.5 2765.89 2763.35 2761.76 2761.07
  2760.3 2760.37 2759.55 2759.74    2759    2759    2759    2759 2759.51 2757.15
  2757.3 2755.96 2755.94 2755.19 2754.79 2754.71 2754.19 2754.55 2755.12 2756.54
 2756.54 2755.63 2755.67 2757.42 2759.85 2760.51  2761.8 2762.26 2762.16 2761.29
 2760.02 2759.39 2759.17 2758.61 2759.68 2763.83 2764.64 2765.84 2768.02 2768.73
    2732    2732    2732    2732    2732    2732    2732    2732    2732    2732
    2732    2732    2732    2732    2732    2732    2732    2732    2732    2732
    2732    2732    2732    2732    2732    2757    2757    2732    2732    2732
    2732    2732    2732    2732    2732    2732    2732    2732    2732    2732
    2732    2732    2732    2732    2732    2732    2732    2732    2732    2732
    2732    2732    2732    2732    2732    2732    2732    2732    2732    2732
BR Coef= 1 , 1 , 0 ,1.25, 0 ,,,0.8,0,2,0,
WSPro=,,,, 1 ,,,, 0 ,,,, 0 ,,,,-1 ,-1 ,-1 , 0 , 0 , 0 , 0 , 0
BC Design=,, 0 ,, 0 ,,,,,,
BC HTab HWMax=2783.55

Type RM Length L Ch R = 1 ,2301    ,270,270,270
BEGIN DESCRIPTION:
XS37
END DESCRIPTION:
XS GIS Cut Line= 5
       804322.92        653699.1       804553.49       653679.01
       804795.12       653653.48       804914.25       653636.85
       804902.27       652642.48
#Sta/Elev= 30
  4506.5 2783.34  4540.2 2788.14  4581.8  2785.5  4601.2 2782.04    4617 2773.87
  4625.2 2770.93  4641.4 2770.93  4664.6 2767.03  4716.1 2762.33  4968.9 2755.58
  4990.6 2753.91    4992 2752.75    4996 2751.75    5000 2751.75    5008 2752.75
  5011.1 2754.37  5019.5 2754.39  5101.2 2752.75  5132.1 2753.92  5206.5  2753.3
  5300.2 2755.35  5340.8 2754.53  5483.2 2757.14  5518.9 2759.59  5567.8 2760.34
  5608.1 2759.59  5948.2 2761.11  6018.2 2758.03    6064  2764.9  6095.6 2766.58
#Mann= 5 ,-1 , 0
  4506.5     .05       0  4968.9    .045       0    4992     .04       0
    5000    .045       0  5019.5     .05       0
#XS Ineff= 2 , 0
       0  4969.9 2759.65  5127.5       0    2775
Permanent Ineff=
       F       F
Bank Sta=4992,5008
Exp/Cntr=0.5,0.3

Type RM Length L Ch R = 1 ,2031    ,216,216,216
BEGIN DESCRIPTION:
XS38
END DESCRIPTION:
XS GIS Cut Line= 5
       804948.51       653935.15       804982.19       653857.26
       804990.62       653714.09       805085.36       653629.87
       805127.47       653225.64
#Sta/Elev= 30
  4859.8 2766.61  4862.3 2766.38  4863.9 2765.79  4875.8 2760.16  4889.8 2754.91
  4901.5 2752.65  4918.9 2750.38  4932.2 2749.55  4972.1 2748.65  4979.2 2748.56
  4988.2 2745.58  4994.7 2743.78  5005.3 2743.78  5007.8 2745.56  5011.5 2747.85
  5019.9 2749.63    5024  2749.8  5091.1 2751.08  5147.5 2749.72  5186.9 2749.93
  5194.4 2750.72  5214.9 2749.56  5231.8 2749.65  5284.1 2748.84    5412 2750.23
  5464.5 2752.23  5488.9 2752.19  5514.6 2752.75  5535.6 2754.08  5621.3 2754.15
#Mann= 5 ,-1 , 0
  4859.8    .035       0  4972.1    .045       0  4988.2     .04       0
  5007.8    .045       0    5024     .03       0
#XS Ineff= 2 , 0
       0    4952    2755  5086.4       0    2755
Permanent Ineff=
       T       T
#Block Obstruct= 2 ,-1
    4950    4915    2755    5136    5180    2755
Bank Sta=4988.2,5007.8
Exp/Cntr=0.5,0.3

Type RM Length L Ch R = 1 ,1815    ,34,34,34
BEGIN DESCRIPTION:
XS 38.7
END DESCRIPTION:
XS GIS Cut Line= 5
       805179.51       653966.03       805200.23       653847.37
       805196.46       653642.08       805194.58       653478.22
       805160.68       653246.56
#Sta/Elev= 30
  4854.5 2763.37  4869.8 2757.22  4883.1 2752.92  4894.3  2750.3  4914.8 2746.34
  4935.2 2743.91  4946.2 2743.39  4973.6 2743.08    4978    2743  4988.2 2741.54
  4992.3 2740.02  4996.4  2738.4  5004.3  2738.4  5007.8 2740.02  5024.8 2743.54
  5029.1 2743.65    5098 2744.13  5124.5  2744.7  5135.9 2745.57    5158 2745.94
    5249 2746.53  5275.5 2746.26  5339.7 2748.19  5361.6 2749.19  5368.6 2750.04
  5391.4 2750.37  5436.1 2751.94  5491.5  2752.7  5515.6 2754.16  5578.3 2754.75
#Mann= 5 ,-1 , 0
  4854.5    .035       0  4973.6    .045       0  4992.3     .04       0
  5007.8    .045       0  5029.1     .03       0
#XS Ineff= 2 , 0
       0    4979 2743.44    5021       0  2743.1
Permanent Ineff=
       F       F
Bank Sta=4992.3,5007.8
Exp/Cntr=0.5,0.3

Type RM Length L Ch R = 3 ,1798    ,,,
BEGIN DESCRIPTION:
XS39 TOR
Structure ID: XS39
Approximate Survey Structure
END DESCRIPTION:
Bridge Culvert--1,0,-1,-1, 0
Deck Dist Width WeirC Skew NumUp NumDn MinLoCord MaxHiCord MaxSubmerge Is_Ogee
11,12,3,0, 48, 48, , , , 0, 1,1,,
    4849  4853.8  4862.1  4865.8  4876.9  4888.8  4902.2  4906.2  4915.9  4921.3
  4927.9  4938.7  4948.7  4956.8  4968.2  4978.1  4987.5  4987.5  5012.5  5012.5
  5030.8  5040.2    5053  5082.6  5095.8  5105.8  5124.5  5133.5  5149.7    5168
  5192.1  5200.7  5207.6  5238.7  5247.3  5285.4  5297.5  5313.6  5339.1    5385
  5402.6  5413.6  5450.4  5491.2  5511.3    5516  5528.2  5578.1
 2766.17 2764.31 2760.82  2759.1 2755.09 2751.68 2748.53 2747.77 2746.11 2745.34
 2744.28 2743.44 2743.08 2743.06 2743.17 2743.37    2744    2744    2744    2744
    2744 2743.67 2743.47 2743.81 2744.12 2744.26 2744.72 2744.79  2745.2 2745.77
 2746.15 2746.09  2746.2 2746.07 2746.13 2745.83 2746.56 2747.04 2748.06 2750.58
 2750.87 2750.95 2751.98 2752.91 2754.15  2754.3 2754.28  2754.7
    2716    2716    2716    2716    2716    2716    2716    2716    2716    2716
    2716    2716    2716    2716    2716    2716    2716    2742    2742    2716
    2716    2716    2716    2716    2716    2716    2716    2716    2716    2716
    2716    2716    2716    2716    2716    2716    2716    2716    2716    2716
    2716    2716    2716    2716    2716    2716    2716    2716
    4849  4853.8  4862.1  4865.8  4876.9  4888.8  4902.2  4906.2  4915.9  4921.3
  4927.9  4938.7  4948.7  4956.8  4968.2  4978.1  4987.5  4987.5  5012.5  5012.5
  5030.8  5040.2    5053  5082.6  5095.8  5105.8  5124.5  5133.5  5149.7    5168
  5192.1  5200.7  5207.6  5238.7  5247.3  5285.4  5297.5  5313.6  5339.1    5385
  5402.6  5413.6  5450.4  5491.2  5511.3    5516  5528.2  5578.1
 2766.17 2764.31 2760.82  2759.1 2755.09 2751.68 2748.53 2747.77 2746.11 2745.34
 2744.28 2743.44 2743.08 2743.06 2743.17 2743.37    2744    2744    2744    2744
    2744 2743.67 2743.47 2743.81 2744.12 2744.26 2744.72 2744.79  2745.2 2745.77
 2746.15 2746.09  2746.2 2746.07 2746.13 2745.83 2746.56 2747.04 2748.06 2750.58
 2750.87 2750.95 2751.98 2752.91 2754.15  2754.3 2754.28  2754.7
    2716    2716    2716    2716    2716    2716    2716    2716    2716    2716
    2716    2716    2716    2716    2716    2716    2716    2742    2742    2716
    2716    2716    2716    2716    2716    2716    2716    2716    2716    2716
    2716    2716    2716    2716    2716    2716    2716    2716    2716    2716
    2716    2716    2716    2716    2716    2716    2716    2716
BR Coef= 1 , 1 , 0 ,1.25, 0 ,,,0.8,0,2,0,
WSPro=,,,, 1 ,,,, 0 ,,,, 0 ,,,,-1 ,-1 ,-1 , 0 , 0 , 0 , 0 , 0
BC Design=,, 0 ,, 0 ,,,,,,
BC HTab HWMax=2763.37

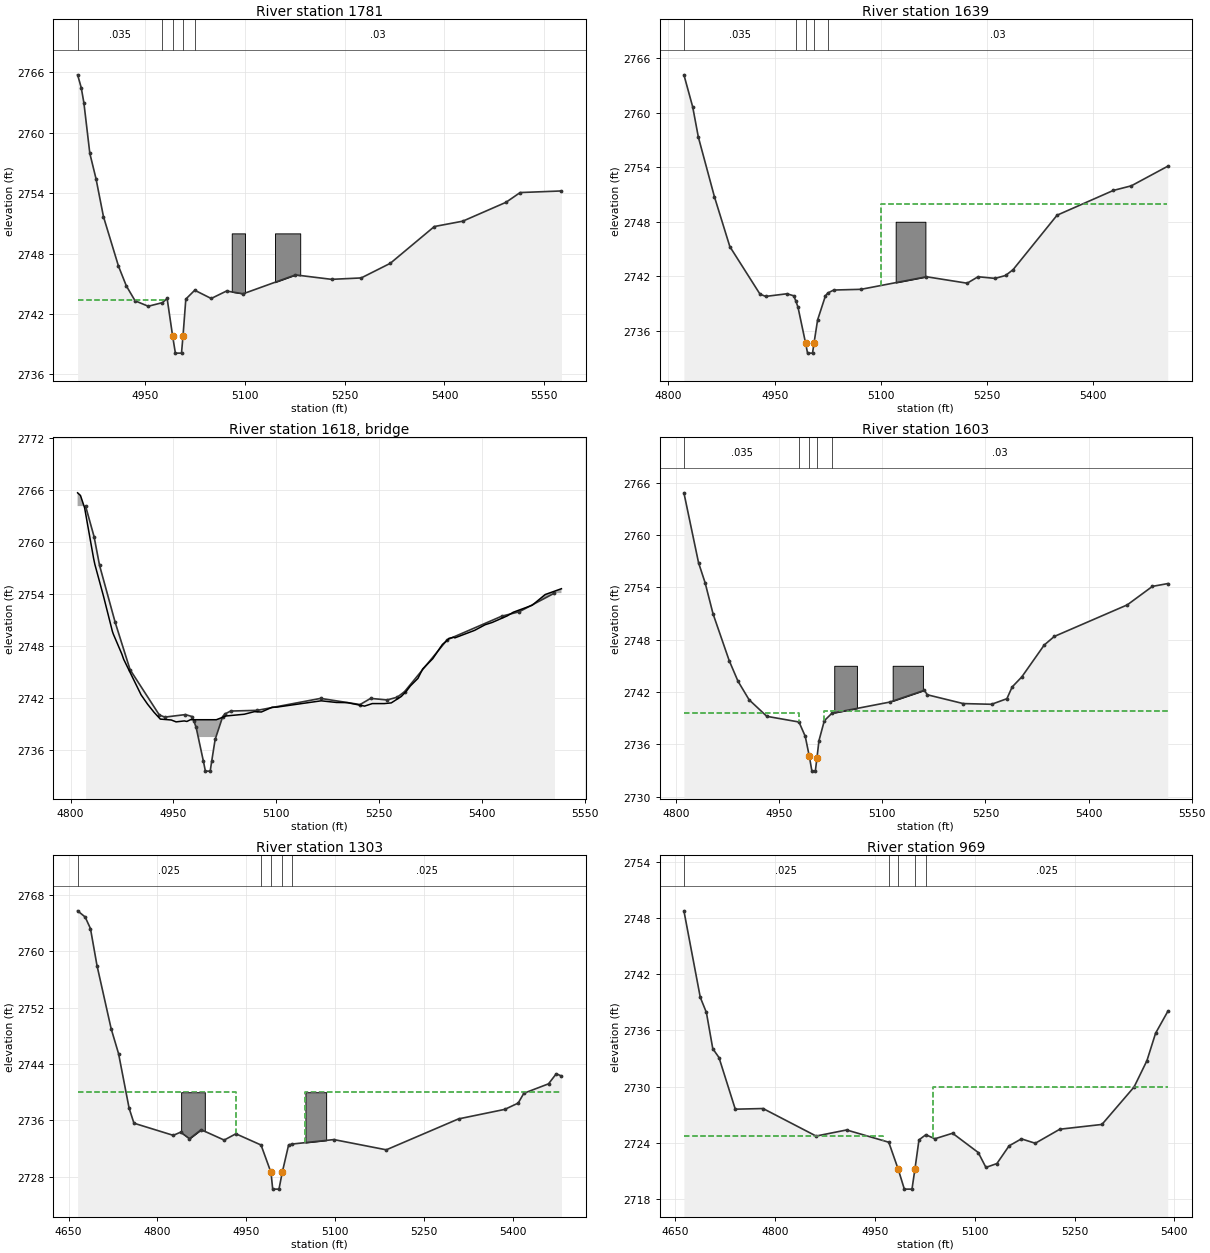
Type RM Length L Ch R = 1 ,1781    ,142,142,142
BEGIN DESCRIPTION:
XS 39.3
END DESCRIPTION:
XS GIS Cut Line= 4
       805213.42       653971.68       805234.13       653847.37
        805226.6       653472.57       805190.81       653248.45
#Sta/Elev= 30
  4848.1 2765.73  4853.5 2764.47  4857.5 2762.98  4866.5 2757.93  4875.8 2755.42
    4887 2751.66  4909.6 2746.75  4921.4 2744.79  4934.6 2743.31  4954.4 2742.77
  4975.8 2743.13  4982.8 2743.54  4991.1 2739.79  4995.2 2738.12  5004.4 2738.12
  5006.7 2739.84  5010.9 2743.48  5024.3 2744.36  5049.1 2743.54  5072.1 2744.28
  5097.2 2744.01  5175.8 2745.88  5230.2 2745.44  5274.8 2745.58  5318.5 2747.03
  5384.8 2750.68  5427.5 2751.21  5492.5 2753.08  5513.9 2754.05    5576 2754.21
#Mann= 5 ,-1 , 0
  4848.1    .035       0  4975.8    .045       0  4991.1     .04       0
  5006.7    .045       0  5024.3     .03       0
#XS Ineff= 2 , 0
       0    4979 2743.44    5021       0  2743.1
Permanent Ineff=
       F       F
#Block Obstruct= 2 ,-1
    5080    5100    2750    5145    5183    2750
Bank Sta=4991.1,5006.7
Exp/Cntr=0.5,0.3

Type RM Length L Ch R = 1 ,1639    ,36,36,36
BEGIN DESCRIPTION:
XS 39.7
END DESCRIPTION:
XS GIS Cut Line= 5
       805356.56        653969.8       805375.39       653809.71
       805369.74       653772.04       805354.67       653534.73
        805260.5       653306.83
#Sta/Elev= 30
  4821.8 2764.14  4834.2 2760.62  4842.2  2757.3  4864.9 2750.75  4886.7 2745.27
  4929.3 2740.05  4937.3  2739.8  4967.3 2740.09  4976.9 2739.87  4979.7 2739.35
    4983 2738.61  4993.6 2734.71  4996.5 2733.57  5003.5 2733.57  5005.7 2734.71
  5010.7 2737.22  5021.8 2739.87  5025.1 2740.17  5033.4  2740.5  5072.2 2740.58
  5164.5 2741.96    5222 2741.25  5237.4 2741.96  5261.4 2741.78  5276.3  2742.1
  5286.9 2742.74    5349 2748.72  5428.5 2751.44    5454 2751.95  5505.4  2754.1
#Mann= 5 ,-1 , 0
  4821.8    .035       0  4979.7    .045       0  4993.6     .04       0
  5005.7    .045       0  5025.1     .03       0
#XS Ineff= 3 ,-1
  4821.8  4975.5  2738.2  5024.5  5099.5 2739.87    5100  5504.2    2750
Permanent Ineff=
       F       F       F
#Block Obstruct= 1 ,-1
    5121    5163    2748
Bank Sta=4993.6,5005.7
Exp/Cntr=0.5,0.3

Type RM Length L Ch R = 3 ,1618    ,,,
BEGIN DESCRIPTION:
XS40 TOR
Structure ID: XS40
Approximate Survey Structure
END DESCRIPTION:
Bridge Culvert--1,0,-1,-1, 0
Deck Dist Width WeirC Skew NumUp NumDn MinLoCord MaxHiCord MaxSubmerge Is_Ogee
18,6,3,0, 55, 55, , , , 0, 1,1,,
  4810.2  4814.4  4820.4  4833.5  4835.3    4848  4860.9  4862.2  4874.7  4877.4
  4902.8  4912.3  4921.6  4930.8  4946.7  4953.8  4965.7  4969.5  4974.7  4987.5
  4987.5  5012.5  5012.5  5026.5  5053.1  5067.9  5078.1  5093.8  5100.4  5165.3
  5187.5  5203.4  5228.6  5239.8  5257.2  5267.5  5282.1  5289.9  5295.4  5306.4
  5313.3    5328    5342  5350.1  5351.4  5358.4  5360.2  5389.1  5404.2  5414.7
  5436.7  5445.4  5472.9  5491.9  5515.6
 2765.67 2765.36 2763.94 2758.11 2757.43 2753.73 2749.69 2749.39 2747.07 2746.46
 2742.36 2741.28 2740.36 2739.57 2739.47 2739.25 2739.36  2739.3  2739.5  2739.5
  2739.5  2739.5  2739.5 2739.93 2740.13 2740.43 2740.39 2740.94 2740.95 2741.68
 2741.49 2741.47 2741.07 2741.36 2741.36 2741.44 2742.18 2742.83  2743.4 2744.27
 2745.36 2746.54 2748.18 2748.72 2748.88 2749.01 2748.94 2749.81 2750.45 2750.72
 2751.48  2751.9  2752.7 2753.94 2754.61
    2713    2713    2713    2713    2713    2713    2713    2713    2713    2713
    2713    2713    2713    2713    2713    2713    2713    2713    2713    2713
  2737.5  2737.5    2713    2713    2713    2713    2713    2713    2713    2713
    2713    2713    2713    2713    2713    2713    2713    2713    2713    2713
    2713    2713    2713    2713    2713    2713    2713    2713    2713    2713
    2713    2713    2713    2713    2713
  4810.2  4814.4  4820.4  4833.5  4835.3    4848  4860.9  4862.2  4874.7  4877.4
  4902.8  4912.3  4921.6  4930.8  4946.7  4953.8  4965.7  4969.5  4974.7  4987.5
  4987.5  5012.5  5012.5  5026.5  5053.1  5067.9  5078.1  5093.8  5100.4  5165.3
  5187.5  5203.4  5228.6  5239.8  5257.2  5267.5  5282.1  5289.9  5295.4  5306.4
  5313.3    5328    5342  5350.1  5351.4  5358.4  5360.2  5389.1  5404.2  5414.7
  5436.7  5445.4  5472.9  5491.9  5515.6
 2765.67 2765.36 2763.94 2758.11 2757.43 2753.73 2749.69 2749.39 2747.07 2746.46
 2742.36 2741.28 2740.36 2739.57 2739.47 2739.25 2739.36  2739.3  2739.5  2739.5
  2739.5  2739.5  2739.5 2739.93 2740.13 2740.43 2740.39 2740.94 2740.95 2741.68
 2741.49 2741.47 2741.07 2741.36 2741.36 2741.44 2742.18 2742.83  2743.4 2744.27
 2745.36 2746.54 2748.18 2748.72 2748.88 2749.01 2748.94 2749.81 2750.45 2750.72
 2751.48  2751.9  2752.7 2753.94 2754.61
    2713    2713    2713    2713    2713    2713    2713    2713    2713    2713
    2713    2713    2713    2713    2713    2713    2713    2713    2713    2713
  2737.5  2737.5    2713    2713    2713    2713    2713    2713    2713    2713
    2713    2713    2713    2713    2713    2713    2713    2713    2713    2713
    2713    2713    2713    2713    2713    2713    2713    2713    2713    2713
    2713    2713    2713    2713    2713
Abutment Skew #Up #Dn= , 2 , 2
  4987.5  4990.2
 2737.45 2736.13
  4987.5  4989.8
 2737.48  2736.2
Abutment Skew #Up #Dn= , 2 , 2
  5009.3  5012.5
 2736.41 2737.49
  5009.6  5012.5
 2737.06 2737.51
BR Coef= 1 , 1 , 0 ,1.25, 0 ,,,0.8,0,2,0,
WSPro=,,,, 1 ,,,, 0 ,,,, 0 ,,,,-1 ,-1 ,-1 , 0 , 0 , 0 , 0 , 0
BC Design=,, 0 ,, 0 ,,,,,,
BC HTab HWMax=2764.14

Type RM Length L Ch R = 1 ,1603    ,300,300,300
BEGIN DESCRIPTION:
XS 40.3
END DESCRIPTION:
XS GIS Cut Line= 5
       805382.92       653967.91       805414.94       653817.24
       805399.87       653755.09       805390.46       653527.19
        805294.4         653288.
#Sta/Elev= 30
  4811.3 2764.82  4832.6 2756.81  4842.2  2754.5  4853.7 2750.95  4877.2 2745.59
    4890 2743.23  4906.2  2741.1  4931.9 2739.21  4978.7 2738.56  4987.8 2736.92
  4993.8 2734.61  4997.5 2732.93  5002.5 2732.93  5004.9 2734.47  5007.8 2736.43
  5015.6 2738.71  5026.6 2739.56  5110.7 2740.84  5161.1 2742.19  5165.4 2741.68
  5217.7 2740.67  5258.9 2740.59  5281.2 2741.23  5288.8 2742.57  5302.9 2743.73
  5335.5 2747.38  5350.1 2748.36  5456.3 2751.98  5492.9  2754.1  5515.2 2754.42
#Mann= 5 ,-1 , 0
  4811.3    .035       0  4978.7    .045       0  4993.8     .04       0
  5004.9    .045       0  5026.6     .03       0
#XS Ineff= 2 , 0
       0 4978.22 2739.64 5015.53       0 2739.81
Permanent Ineff=
       F       F
#Block Obstruct= 2 ,-1
    5030    5063    2745    5115    5159    2745
Bank Sta=4993.8,5004.9
Exp/Cntr=0.5,0.3

Type RM Length L Ch R = 1 ,1303    ,334,334,334
BEGIN DESCRIPTION:
XS41
END DESCRIPTION:
XS GIS Cut Line= 6
       805659.21       654066.76       805686.94       653960.75
       805693.46       653766.67       805698.36       653694.91
       805699.99        653504.1       805589.08       653279.03
#Sta/Elev= 30
  4665.1  2765.7  4677.8 2764.83  4686.8 2763.19  4697.9 2757.93  4721.8 2748.99
  4734.3 2745.46  4752.1 2737.74  4760.3 2735.61  4826.7 2733.89  4839.2 2734.34
  4854.1 2733.41  4873.8 2734.69  4912.7 2733.22  4932.5 2734.11    4975 2732.52
  4991.8 2728.63  4994.7 2726.27  5005.3 2726.27  5010.8 2728.63  5021.6 2732.54
  5027.9 2732.66    5098 2733.29  5186.6 2731.84  5308.6 2736.22  5386.8 2737.57
  5409.4 2738.46    5419 2739.85  5460.7 2741.19  5473.8 2742.62  5482.5 2742.29
#Mann= 5 ,-1 , 0
  4665.1    .025       0    4975     .06       0  4991.8     .04       0
  5010.8     .06       0  5027.9    .025       0
#XS Ineff= 2 , 0
       0  4932.5    2740  5048.5       0    2740
Permanent Ineff=
       F       T
#Block Obstruct= 2 ,-1
    4840    4880    2740    5050    5085    2740
Bank Sta=4991.8,5010.8
Exp/Cntr=0.5,0.3

Type RM Length L Ch R = 1 ,969     ,60,60,60
BEGIN DESCRIPTION:
XS42
END DESCRIPTION:
XS GIS Cut Line= 6
       805994.64        654046.4        806010.4       653964.95
       806037.27       653835.42       806007.57       653628.28
       805997.26       653436.86       806105.06       653410.44
#Sta/Elev= 30
  4662.9 2748.77  4687.5 2739.53  4696.7 2737.91  4706.3 2734.04  4715.6  2733.1
  4740.1 2727.58  4781.9 2727.65  4861.6 2724.71  4907.4 2725.36  4970.8 2724.05
  4985.1 2721.14  4994.2 2719.04  5005.7 2719.04  5010.1 2721.17  5016.2  2724.3
  5026.5 2724.85  5040.2 2724.42  5066.7 2725.01  5105.3 2722.95  5116.8 2721.36
  5133.3 2721.77  5151.6 2723.66  5170.1 2724.41    5191 2723.94  5227.9 2725.44
  5291.2 2725.95  5339.5 2729.95  5358.8 2732.76  5371.8 2735.69  5390.1 2738.02
#Mann= 5 ,-1 , 0
  4662.9    .025       0  4970.8     .06       0  4985.1     .04       0
  5010.1     .06       0  5026.5    .025       0
#XS Ineff= 2 , 0
       0  4962.5 2724.76  5037.5       0    2730
Permanent Ineff=
       F       F
Bank Sta=4985.1,5010.1
Exp/Cntr=0.5,0.3

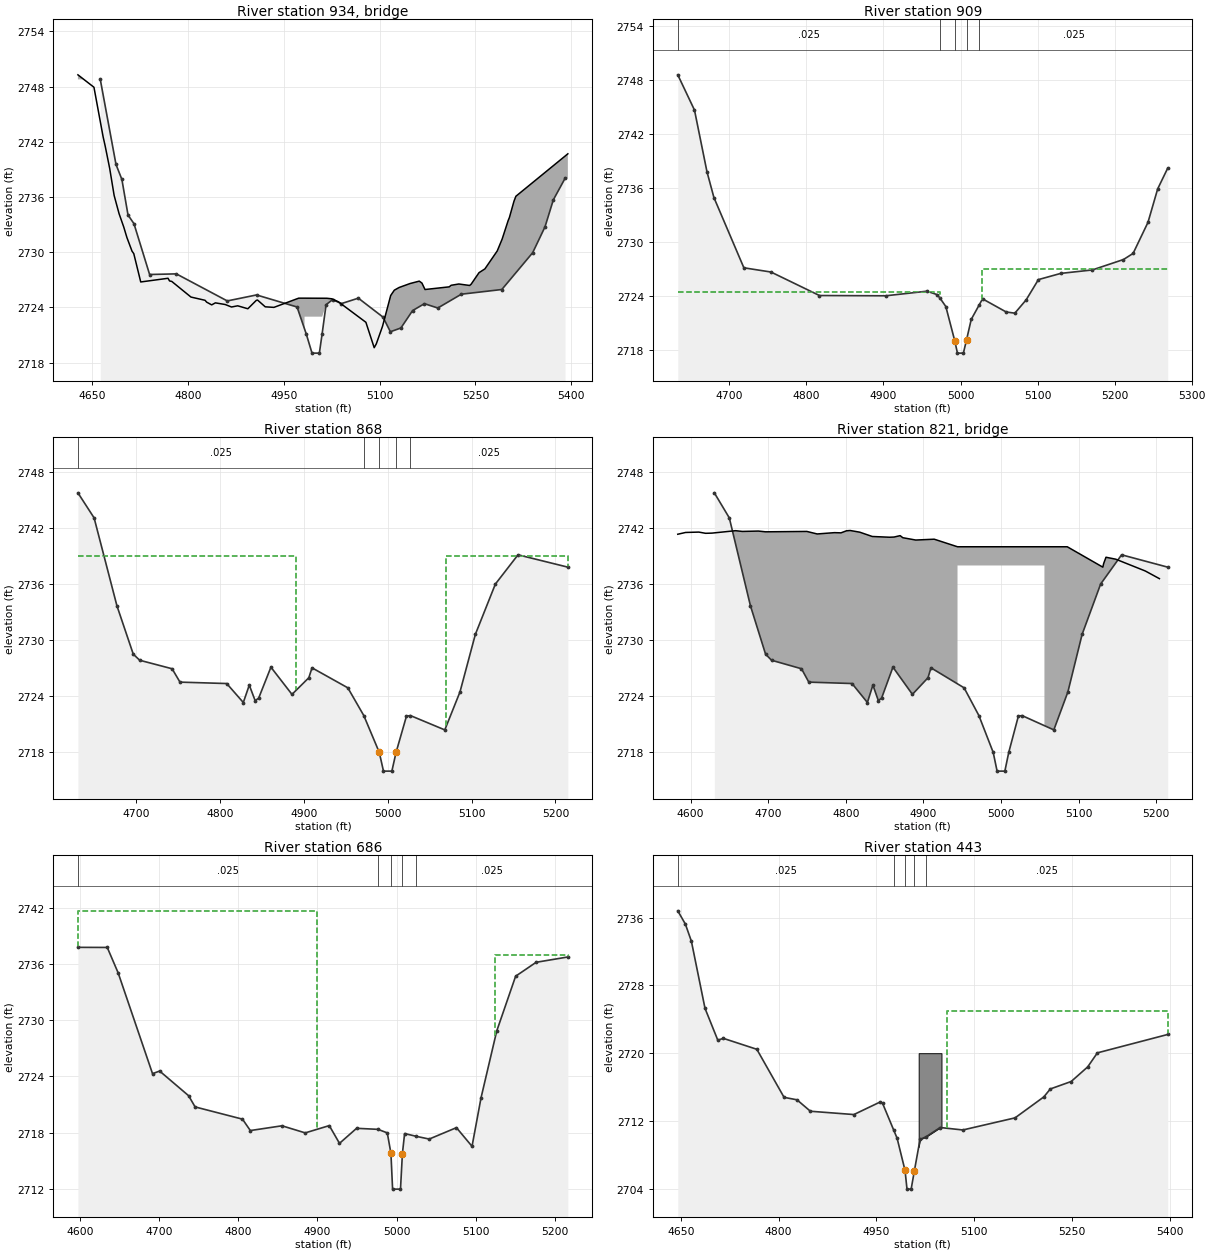
Type RM Length L Ch R = 3 ,934     ,,,
BEGIN DESCRIPTION:
XS43 TOR
Structure ID: XS43
Approximate Survey Structure
END DESCRIPTION:
Bridge Culvert--1,0,-1,-1, 0
Deck Dist Width WeirC Skew NumUp NumDn MinLoCord MaxHiCord MaxSubmerge Is_Ogee
20,30,3,0, 60, 60, , , , 0, 1,1,,
  4627.9    4653  4667.3  4670.7  4677.6  4684.6  4692.3  4699.7  4704.5  4712.6
  4715.3  4726.2  4768.9  4771.3  4774.7  4804.8  4826.8  4829.3  4837.2    4843
  4858.4  4868.2  4877.9  4893.8    4907  4908.9    4921  4934.6  4973.3  4982.5
  4982.5  5017.5  5017.5  5025.3  5035.6  5078.5  5091.5  5094.8  5104.5  5117.3
    5123  5130.5  5147.6    5162  5166.2    5171  5208.9  5211.9  5223.9  5240.8
  5243.2  5255.5  5264.7    5284  5291.7  5301.1    5303  5310.2  5313.2  5394.5
 2749.27 2747.92 2742.55 2741.49 2739.11 2736.16 2734.19 2732.72 2731.61 2730.11
 2729.85 2726.77 2727.17 2726.88 2726.83 2725.13 2724.78 2724.58 2724.28  2724.5
 2724.32 2724.05 2724.18 2723.86 2724.77 2724.81 2724.07 2724.01 2725.01 2725.01
 2725.01    2725    2725 2724.94 2724.61 2722.39 2719.63 2720.05 2721.95  2725.3
 2725.88 2726.17  2726.6 2726.86 2726.65 2725.95 2726.24 2726.41 2726.55 2726.39
 2726.53 2727.78 2728.19 2730.14 2731.43 2733.44 2733.76 2735.54 2736.08 2740.69
    2698    2698    2698    2698    2698    2698    2698    2698    2698    2698
    2698    2698    2698    2698    2698    2698    2698    2698    2698    2698
    2698    2698    2698    2698    2698    2698    2698    2698    2698    2698
    2723    2723    2698    2698    2698    2698    2698    2698    2698    2698
    2698    2698    2698    2698    2698    2698    2698    2698    2698    2698
    2698    2698    2698    2698    2698    2698    2698    2698    2698    2698
  4627.9    4653  4667.3  4670.7  4677.6  4684.6  4692.3  4699.7  4704.5  4712.6
  4715.3  4726.2  4768.9  4771.3  4774.7  4804.8  4826.8  4829.3  4837.2    4843
  4858.4  4868.2  4877.9  4893.8    4907  4908.9    4921  4934.6  4973.3  4982.5
  4982.5  5017.5  5017.5  5025.3  5035.6  5078.5  5091.5  5094.8  5104.5  5117.3
    5123  5130.5  5147.6    5162  5166.2    5171  5208.9  5211.9  5223.9  5240.8
  5243.2  5255.5  5264.7    5284  5291.7  5301.1    5303  5310.2  5313.2  5394.5
 2749.27 2747.92 2742.55 2741.49 2739.11 2736.16 2734.19 2732.72 2731.61 2730.11
 2729.85 2726.77 2727.17 2726.88 2726.83 2725.13 2724.78 2724.58 2724.28  2724.5
 2724.32 2724.05 2724.18 2723.86 2724.77 2724.81 2724.07 2724.01 2725.01 2725.01
 2725.01    2725    2725 2724.94 2724.61 2722.39 2719.63 2720.05 2721.95  2725.3
 2725.88 2726.17  2726.6 2726.86 2726.65 2725.95 2726.24 2726.41 2726.55 2726.39
 2726.53 2727.78 2728.19 2730.14 2731.43 2733.44 2733.76 2735.54 2736.08 2740.69
    2698    2698    2698    2698    2698    2698    2698    2698    2698    2698
    2698    2698    2698    2698    2698    2698    2698    2698    2698    2698
    2698    2698    2698    2698    2698    2698    2698    2698    2698    2698
    2723    2723    2698    2698    2698    2698    2698    2698    2698    2698
    2698    2698    2698    2698    2698    2698    2698    2698    2698    2698
    2698    2698    2698    2698    2698    2698    2698    2698    2698    2698
Abutment Skew #Up #Dn= , 2 , 2
  4982.5  4987.5
 2722.89 2719.86
  4982.5  4985.8
 2723.02 2721.46
Abutment Skew #Up #Dn= , 2 , 2
  5012.5  5017.5
 2722.85    2722
  5014.1  5017.5
  2721.5 2723.06
BR Coef= 1 , 1 , 0 ,1.25, 0 ,,,0.8,0,2,0,
WSPro=,,,, 1 ,,,, 0 ,,,, 0 ,,,,-1 ,-1 ,-1 , 0 , 0 , 0 , 0 , 0
BC Design=,, 0 ,, 0 ,,,,,,
BC HTab HWMax=2748.77

Type RM Length L Ch R = 1 ,909     ,41,41,41
BEGIN DESCRIPTION:
XS44
END DESCRIPTION:
XS GIS Cut Line= 6
       806062.95       654051.65       806076.08       653967.58
        806082.2       653824.75       806068.49       653638.94
       806047.18       653476.27       806102.36       653460.51
#Sta/Elev= 30
    4633  2748.6  4654.7 2744.68  4670.9 2737.83  4679.9 2734.97  4718.8 2727.16
    4754 2726.69  4816.9 2724.08  4902.9 2724.05  4956.4 2724.56  4969.7 2724.18
  4973.5 2723.77  4980.9 2722.86  4992.5 2719.05    4996 2717.68  5003.7 2717.68
  5007.8 2719.15  5013.9 2721.43  5024.2 2723.03  5028.6 2723.71  5059.3 2722.25
  5070.5 2722.12  5085.2  2723.6  5101.1 2725.85  5130.2 2726.54    5171 2726.92
  5211.5 2728.08    5224 2728.76  5243.3 2732.21  5255.9 2735.93  5268.9 2738.23
#Mann= 5 ,-1 , 0
    4633    .025       0  4973.5     .06       0  4992.5     .04       0
  5007.8     .06       0  5024.2    .025       0
#XS Ineff= 2 , 0
       0 4973.51  2724.5 5027.78       0    2727
Permanent Ineff=
       F       T
Bank Sta=4992.5,5007.8
Exp/Cntr=0.5,0.3

Type RM Length L Ch R = 1 ,868     ,182,182,182
BEGIN DESCRIPTION:
XS45
END DESCRIPTION:
XS GIS Cut Line= 6
       806168.04       654041.15       806136.51       653883.51
       806110.24       653662.81        806097.1       653591.87
       806131.26       653502.55       806141.77       653471.02
#Sta/Elev= 30
  4630.7 2745.77    4650 2743.09  4677.2 2733.69  4696.7 2728.51  4704.4 2727.86
    4743 2726.95  4752.4 2725.52  4808.1 2725.37  4827.9 2723.34    4835  2725.2
    4842 2723.54  4846.2 2723.81  4860.8 2727.12  4885.9 2724.21    4906 2725.99
  4909.8 2727.05  4952.5 2724.91  4971.5 2721.95    4990    2718    4995    2716
    5005    2716    5010    2718  5022.4 2721.88  5027.2 2721.94  5068.1 2720.41
  5086.2 2724.47  5104.5 2730.62  5128.4 2736.01  5155.4 2739.14  5214.8 2737.82
#Mann= 5 ,-1 , 0
  4630.7    .025       0  4971.5     .07       0    4990     .05       0
    5010     .07       0  5027.2    .025       0
#XS Ineff= 2 , 0
       0    4891    2739    5070       0    2739
Permanent Ineff=
       F       F
Bank Sta=4990,5010
Exp/Cntr=0.5,0.3

Type RM Length L Ch R = 3 ,821     ,,,
BEGIN DESCRIPTION:
XS46 TOR
Structure ID: XS46
Approximate Survey Structure
END DESCRIPTION:
Bridge Culvert--1,0,-1,-1, 0
Deck Dist Width WeirC Skew NumUp NumDn MinLoCord MaxHiCord MaxSubmerge Is_Ogee
25,44,3,0, 34, 34, , , , 0, 1,1,,
  4583.6  4593.7  4610.7  4619.4  4627.6  4658.1  4666.8  4687.4  4696.6  4749.9
  4763.2  4785.4  4793.9    4801  4805.7  4818.1  4834.2  4856.5  4862.2  4870.1
  4873.5  4890.2    4914    4944    4944    5056    5056  5085.4  5131.2  5132.3
  5135.3  5147.9  5185.9  5204.1
 2741.34 2741.53 2741.57 2741.44 2741.46 2741.72 2741.64 2741.68  2741.6 2741.64
 2741.37 2741.51 2741.49 2741.71 2741.74 2741.56  2741.1 2741.02 2741.04 2741.19
 2740.97 2740.72 2740.81    2740    2740    2740    2740    2740 2737.82 2738.21
 2738.88 2738.67 2737.41 2736.59
 2695.93 2695.93 2695.93 2695.93 2695.93 2695.93 2695.93 2695.93 2695.93 2695.93
 2695.93 2695.93 2695.93 2695.93 2695.93 2695.93 2695.93 2695.93 2695.93 2695.93
 2695.93 2695.93 2695.93 2695.93    2738    2738 2695.93 2695.93 2695.93 2695.93
 2695.93 2695.93 2695.93 2695.93
  4583.6  4593.7  4610.7  4619.4  4627.6  4658.1  4666.8  4687.4  4696.6  4749.9
  4763.2  4785.4  4793.9    4801  4805.7  4818.1  4834.2  4856.5  4862.2  4870.1
  4873.5  4890.2    4914    4944    4944    5056    5056  5085.4  5131.2  5132.3
  5135.3  5147.9  5185.9  5204.1
 2741.34 2741.53 2741.57 2741.44 2741.46 2741.72 2741.64 2741.68  2741.6 2741.64
 2741.37 2741.51 2741.49 2741.71 2741.74 2741.56  2741.1 2741.02 2741.04 2741.19
 2740.97 2740.72 2740.81    2740    2740    2740    2740    2740 2737.82 2738.21
 2738.88 2738.67 2737.41 2736.59
 2695.93 2695.93 2695.93 2695.93 2695.93 2695.93 2695.93 2695.93 2695.93 2695.93
 2695.93 2695.93 2695.93 2695.93 2695.93 2695.93 2695.93 2695.93 2695.93 2695.93
 2695.93 2695.93 2695.93 2695.93    2738    2738 2695.93 2695.93 2695.93 2695.93
 2695.93 2695.93 2695.93 2695.93
BR Coef= 1 , 1 , 0 ,1.25, 0 ,,,0.8,0,2,0,
WSPro=,,,, 1 ,,,, 0 ,,,, 0 ,,,,-1 ,-1 ,-1 , 0 , 0 , 0 , 0 , 0
BC Design=,, 0 ,, 0 ,,,,,,
BC HTab HWMax=2745.77

Type RM Length L Ch R = 1 ,686     ,243,243,243
BEGIN DESCRIPTION:
XS47
END DESCRIPTION:
XS GIS Cut Line= 5
       806354.58       654067.42       806351.95       653967.58
       806315.17       653762.65       806273.13       653583.99
       806204.82       653476.27
#Sta/Elev= 30
  4597.3 2737.82  4634.4 2737.81  4648.2 2735.08  4691.6  2724.3  4700.6 2724.58
  4737.2 2721.94  4745.4 2720.74  4805.3 2719.43  4815.2 2718.21  4855.2 2718.72
  4884.6 2717.96    4915 2718.74  4927.9 2716.84  4949.5 2718.45  4976.5 2718.34
  4988.3 2717.96  4992.9 2715.78    4995 2711.94    5005 2711.94  5007.4 2715.74
  5010.2 2717.89    5025 2717.59  5041.3  2717.3  5075.7 2718.52  5095.4 2716.52
  5106.8 2721.72  5126.6 2728.86  5150.5 2734.73  5176.4 2736.22  5216.5 2736.79
#Mann= 5 ,-1 , 0
  4597.3    .025       0  4976.5     .07       0  4992.9     .05       0
  5007.4     .07       0    5025    .025       0
#XS Ineff= 2 , 0
       0    4900 2741.73    5125       0 2736.95
Permanent Ineff=
       F       F
Bank Sta=4992.9,5007.4
Exp/Cntr=0.5,0.3

Type RM Length L Ch R = 1 ,443     ,191,191,191
BEGIN DESCRIPTION:
XS48
END DESCRIPTION:
XS GIS Cut Line= 6
       806425.75       654060.08       806511.86       653820.01
        806494.9       653754.77       806519.69       653689.53
       806539.26       653613.86       806428.14       653355.42
#Sta/Elev= 30
  4645.4  2736.8  4657.1 2735.23  4666.3 2733.21  4687.2 2725.29  4706.8 2721.54
  4715.4 2721.75  4766.7 2720.46  4808.5 2714.79  4828.3  2714.5  4848.9 2713.15
  4915.6 2712.76  4955.3 2714.22  4959.6 2714.09  4976.8 2710.91  4981.9 2709.97
  4994.1 2706.16  4997.1 2703.96  5003.5 2703.97  5008.4 2706.11  5017.1 2709.82
  5026.4 2710.14    5048 2711.23  5082.8 2710.94  5162.9 2712.37    5207 2714.84
    5217 2715.78    5249 2716.66  5274.3 2718.38  5289.2 2720.04  5397.1 2722.21
#Mann= 5 ,-1 , 0
  4645.4    .025       0  4976.8     .07       0  4994.1     .05       0
  5008.4     .07       0  5026.4    .025       0
#XS Ineff= 2 , 0
       0                    5059       0    2725
Permanent Ineff=
       F       T
#Block Obstruct= 1 ,-1
    5015    5050    2720
Bank Sta=4994.1,5008.4
Exp/Cntr=0.5,0.3

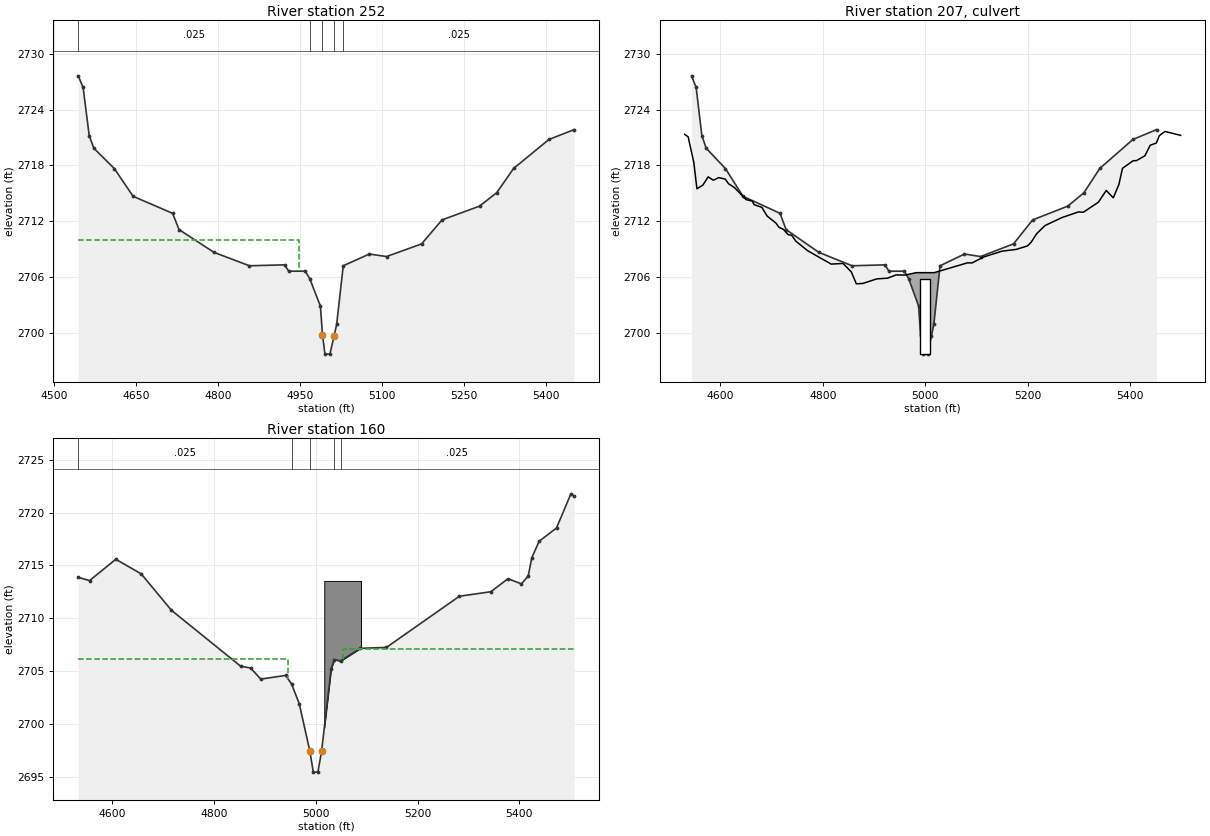
Type RM Length L Ch R = 1 ,252     ,92,92,92
BEGIN DESCRIPTION:
XS49
END DESCRIPTION:
XS GIS Cut Line= 6
       806535.97       654067.79       806767.77       653856.95
       806660.88       653697.96       806624.37       653615.76
       806581.89       653482.99        806468.6       653351.96
#Sta/Elev= 30
    4544 2727.62    4553 2726.37  4564.1 2721.21  4572.6 2719.85  4610.1 2717.67
  4644.5 2714.69  4716.7 2712.87  4728.5 2711.12  4792.4 2708.68  4857.3 2707.24
  4921.6 2707.34  4929.2 2706.66  4959.3 2706.66  4967.6 2705.87 4987.16 2702.92
    4991 2699.81  4995.5 2697.76  5004.5 2697.76  5012.3 2699.73  5016.9 2700.95
    5029 2707.24  5076.7  2708.5  5108.2 2708.23  5172.4 2709.59  5209.7 2712.16
  5278.3 2713.64  5309.7 2715.07  5340.7 2717.68  5405.3 2720.79  5451.5 2721.85
#Mann= 5 ,-1 , 0
    4544    .025       0  4967.6     .07       0    4991     .05       0
  5012.3     .07       0    5029    .025       0
#XS Ineff= 2 , 0
       0    4948    2710    5052       0  2707.1
Permanent Ineff=
       F       F
Bank Sta=4991,5012.3
Exp/Cntr=0.5,0.3

Type RM Length L Ch R = 2 ,207     ,,,
BEGIN DESCRIPTION:
XS50 TOR
Structure ID: XS50
Approximate Survey Structure
END DESCRIPTION:
Bridge Culvert--1,0,-1,-1, 0
Deck Dist Width WeirC Skew NumUp NumDn MinLoCord MaxHiCord MaxSubmerge Is_Ogee
34.5,21,3,0, 60, 60, , , , 0, 1,1,,
  4530.6  4537.4  4548.5  4554.5    4566  4576.5  4586.6  4597.1  4609.7  4616.2
  4627.8  4650.4  4662.4  4666.3  4681.1  4691.6  4708.7  4714.6  4723.4  4732.8
  4739.3  4747.6  4770.4  4816.5  4839.7  4855.7  4865.7  4878.7  4905.3  4926.3
  4943.5  4960.3  4982.5  5017.5  5082.2  5091.6  5113.8  5150.3  5177.9  5199.7
    5207  5217.5    5234  5266.9  5299.2  5308.5    5338  5353.3  5367.1    5378
  5385.1  5405.8  5412.2  5428.8  5439.1  5451.1  5456.8  5461.2  5468.1  5498.5
 2721.34 2721.07  2718.3  2715.5 2715.89 2716.78 2716.42  2716.7 2716.54 2716.04
 2715.63 2714.34 2714.18 2713.79 2713.51 2712.57 2711.82 2711.37 2711.14 2710.57
 2710.52 2709.88 2708.86 2707.42 2707.49 2706.59  2705.3 2705.35 2705.83 2705.91
 2706.26 2706.24  2706.5  2706.5 2707.55 2707.55 2708.18 2708.81    2709 2709.37
 2709.78 2710.68 2711.56 2712.41 2713.02 2712.98 2714.06 2715.32 2714.53 2715.96
  2717.7 2718.51 2718.52 2719.04 2720.17 2720.41 2721.18 2721.39 2721.65 2721.23
    2675    2675    2675    2675    2675    2675    2675    2675    2675    2675
    2675    2675    2675    2675    2675    2675    2675    2675    2675    2675
    2675    2675    2675    2675    2675    2675    2675    2675    2675    2675
    2675    2675    2675    2675    2675    2675    2675    2675    2675    2675
    2675    2675    2675    2675    2675    2675    2675    2675    2675    2675
    2675    2675    2675    2675    2675    2675    2675    2675    2675    2675
  4530.6  4537.4  4548.5  4554.5    4566  4576.5  4586.6  4597.1  4609.7  4616.2
  4627.8  4650.4  4662.4  4666.3  4681.1  4691.6  4708.7  4714.6  4723.4  4732.8
  4739.3  4747.6  4770.4  4816.5  4839.7  4855.7  4865.7  4878.7  4905.3  4926.3
  4943.5  4960.3  4982.5  5017.5  5082.2  5091.6  5113.8  5150.3  5177.9  5199.7
    5207  5217.5    5234  5266.9  5299.2  5308.5    5338  5353.3  5367.1    5378
  5385.1  5405.8  5412.2  5428.8  5439.1  5451.1  5456.8  5461.2  5468.1  5498.5
 2721.34 2721.07  2718.3  2715.5 2715.89 2716.78 2716.42  2716.7 2716.54 2716.04
 2715.63 2714.34 2714.18 2713.79 2713.51 2712.57 2711.82 2711.37 2711.14 2710.57
 2710.52 2709.88 2708.86 2707.42 2707.49 2706.59  2705.3 2705.35 2705.83 2705.91
 2706.26 2706.24  2706.5  2706.5 2707.55 2707.55 2708.18 2708.81    2709 2709.37
 2709.78 2710.68 2711.56 2712.41 2713.02 2712.98 2714.06 2715.32 2714.53 2715.96
  2717.7 2718.51 2718.52 2719.04 2720.17 2720.41 2721.18 2721.39 2721.65 2721.23
    2675    2675    2675    2675    2675    2675    2675    2675    2675    2675
    2675    2675    2675    2675    2675    2675    2675    2675    2675    2675
    2675    2675    2675    2675    2675    2675    2675    2675    2675    2675
    2675    2675    2675    2675    2675    2675    2675    2675    2675    2675
    2675    2675    2675    2675    2675    2675    2675    2675    2675    2675
    2675    2675    2675    2675    2675    2675    2675    2675    2675    2675
BR Coef= 1 , 1 , 0 ,1.25, 0 ,,,0.8,0,2,0,
WSPro=,,,, 1 ,,,, 0 ,,,, 0 ,,,,-1 ,-1 ,-1 , 0 , 0 , 0 , 0 , 0
Culvert=2,8,19,21,0.013,0.4,1,8,1,2697.79,5000,2695.45,5000,Culvert #1  , 0 ,34.5
Culvert Bottom n=0.013
BC Design=,, 0 ,, 0 ,,,,,,
BC HTab HWMax=2727.62

Type RM Length L Ch R = 1 ,160     ,0,0,0
BEGIN DESCRIPTION:
XS51
END DESCRIPTION:
XS GIS Cut Line= 6
       806571.77       654093.06       806835.91       653850.94
       806745.05       653713.32       806682.26       653611.78
       806617.29       653451.12        806508.6       653337.22
#Sta/Elev= 30
  4534.1 2713.88  4556.3 2713.57  4607.9 2715.59  4657.9  2714.2  4717.1 2710.76
  4852.9 2705.47  4872.4  2705.3  4892.4 2704.25    4941  2704.6  4952.8 2703.79
 4967.83 2701.93  4988.6 2697.46  4995.5 2695.45  5004.5 2695.45  5011.7 2697.42
  5030.5 2705.24  5036.7 2706.09  5048.9 2705.97  5087.9 2707.16    5139 2707.25
  5282.2 2712.09    5344 2712.52  5377.5 2713.75  5403.9 2713.26  5417.2    2714
  5424.3 2715.73  5438.7 2717.29  5472.8 2718.55    5501 2721.78  5507.4 2721.56
#Mann= 5 ,-1 , 0
  4534.1    .025       0  4952.8     .07       0  4988.6     .05       0
  5036.7     .07       0  5048.9    .025       0
#XS Ineff= 2 , 0
       0    4946 2706.18    5054       0 2707.14
Permanent Ineff=
       F       F
#Block Obstruct= 1 ,-1
    5017    5089 2713.54
Bank Sta=4988.6,5011.7
Exp/Cntr=0.5,0.3

Chan Stop Cuts=-1
Use User Specified Reach Order=0
User Specified Reach Order=Plott Creek     ,Reach-1